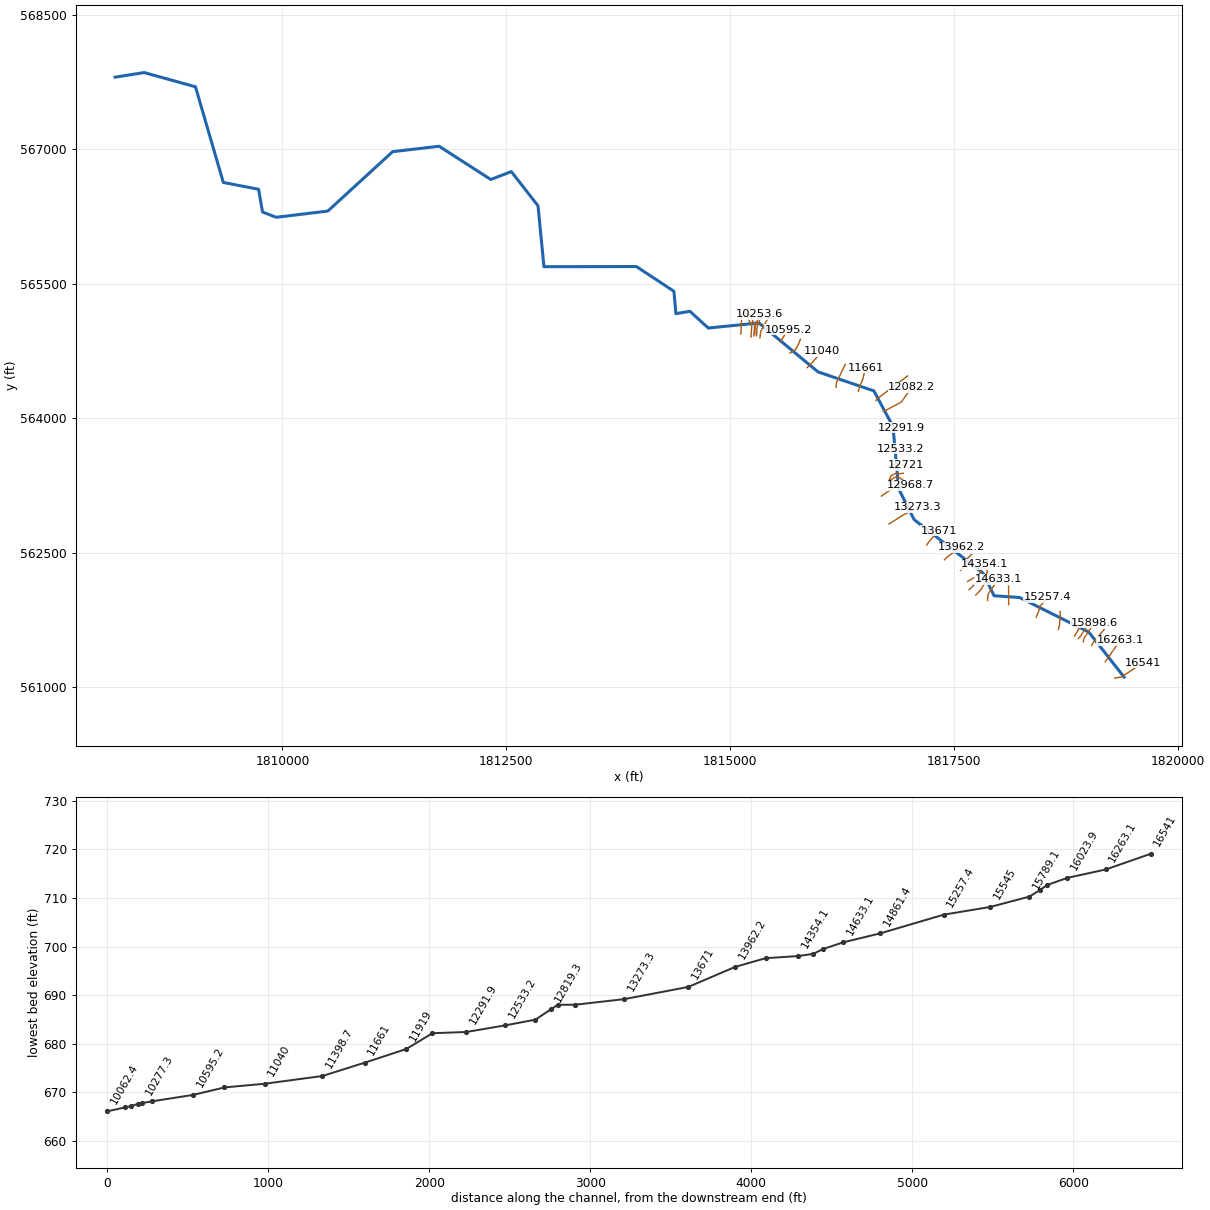
--- LTHRWDCK.prj (project) ---

Proj Title=LTHRWDCK
Current Plan=p01
Default Exp/Contr=0,0
English Units
Geom File=g01
Flow File=f01
Plan File=p01
BEGIN DESCRIPTION:
END DESCRIPTION:
DSS Export Rating Curves= 0
DSS Export Rating Curve Sorted= 0
DSS Export Volume Flow Curves= 0
DXF OffsetX= 0
DXF OffsetY= 0
DXF ScaleX= 0
DXF ScaleY= 0

--- LTHRWDCK.p01 (plan) ---

Plan Title=Floodplain
Program Version=4.00
Geom File=g01
Flow File=f01
K Sum by GR=0
Std Step Tol=0.01
Critical Tol=0.01
Num of Std Step Trials=20
Max Error Tol=0.3
Flow Tol Ratio=0.001
Split Flow NTrial=30
Split Flow Tol=0.02
Split Flow Ratio=0.02
Log Output Level=0
Friction Slope Method=1
Unsteady Friction Slope Method=2
Unsteady Bridges Friction Slope Method=1
Global Log Level=0
CheckData=False
Run HTab=0
Run UNet=0
Run PostProcess=0
UNET Theta=0
UNET Theta Warmup=0
UNET ZTol=0
UNET ZSATol=0
UNET MxIter=0
UNET MaxInSteps=0
UNET DtIC=0
UNET DtMin=0
UNET MaxCRTS=0
UNET WFStab=0
UNET SFStab=0
UNET WFX=0
UNET SFX=0
UNET DSS MLevel=0
UNET DZMax Abort=0
UNET Convert EG Bridges=0
UNET Use Existing IB Tables=0
UNET Froude Limit=0
UNET Froude Power=0
Write IC File=0
Echo Input=False
Echo Output=False
Write Detailed=0

--- LTHRWDCK.f01 (steady flow) ---

Flow Title=NFF Regression Equation
Program Version=4.10
Number of Profiles= 1
Profile Names=P100yr
River Rch & RM=LTHRWDCK,Main            ,16541
971.4059
River Rch & RM=LTHRWDCK,Main            ,14633.1
1008.057
River Rch & RM=LTHRWDCK,Main            ,13962.2
1104.743
River Rch & RM=LTHRWDCK,Main            ,11661
1259.078
River Rch & RM=LTHRWDCK,Main            ,9068.3
1386.836
River Rch & RM=LTHRWDCK,Main            ,8276.1
1455.912
River Rch & RM=LTHRWDCK,Main            ,5904
1519.265
River Rch & RM=LTHRWDCK,Main            ,3039
1602.403
River Rch & RM=LTHRWDCK,Main            ,435.5
1653.423
Boundary for River Rch & Prof#=LTHRWDCK,Main            , 1
Up Type= 0
Dn Type= 3
Dn Slope=0.007
DSS Import GetInterval= 0
DSS Import GetPeak= 0
DSS Import FillOption= 0

--- LTHRWDCK.g01 (geometry) ---

Geom Title=USGS 10m DEM
Program Version=4.10

River Reach=LTHRWDCK        ,Main
Reach XY= 30
     1819395.256      561111.523     1819001.506      561613.606
     1818228.418      561999.452     1817944.563      562018.983
      1817819.16      562272.613     1817051.334      562869.243
     1816879.283      563211.696     1816815.657      563908.306
     1816602.116      564305.441     1815978.642      564517.571
     1815320.866      565063.254     1814753.502      565007.182
     1814548.641      565193.814      1814392.48      565167.421
     1814370.345      565417.421     1813951.074      565693.462
     1812919.211       565691.43     1812853.128      566371.197
     1812554.734      566753.141     1812326.002      566664.817
     1811749.162      567035.828     1811230.516       566975.58
     1810506.557      566312.386     1809930.168      566242.941
     1809777.391      566301.969     1809733.988      566555.441
      1809339.89       566631.83     1809029.127      567699.539
     1808456.251      567858.253     1808132.464      567806.761

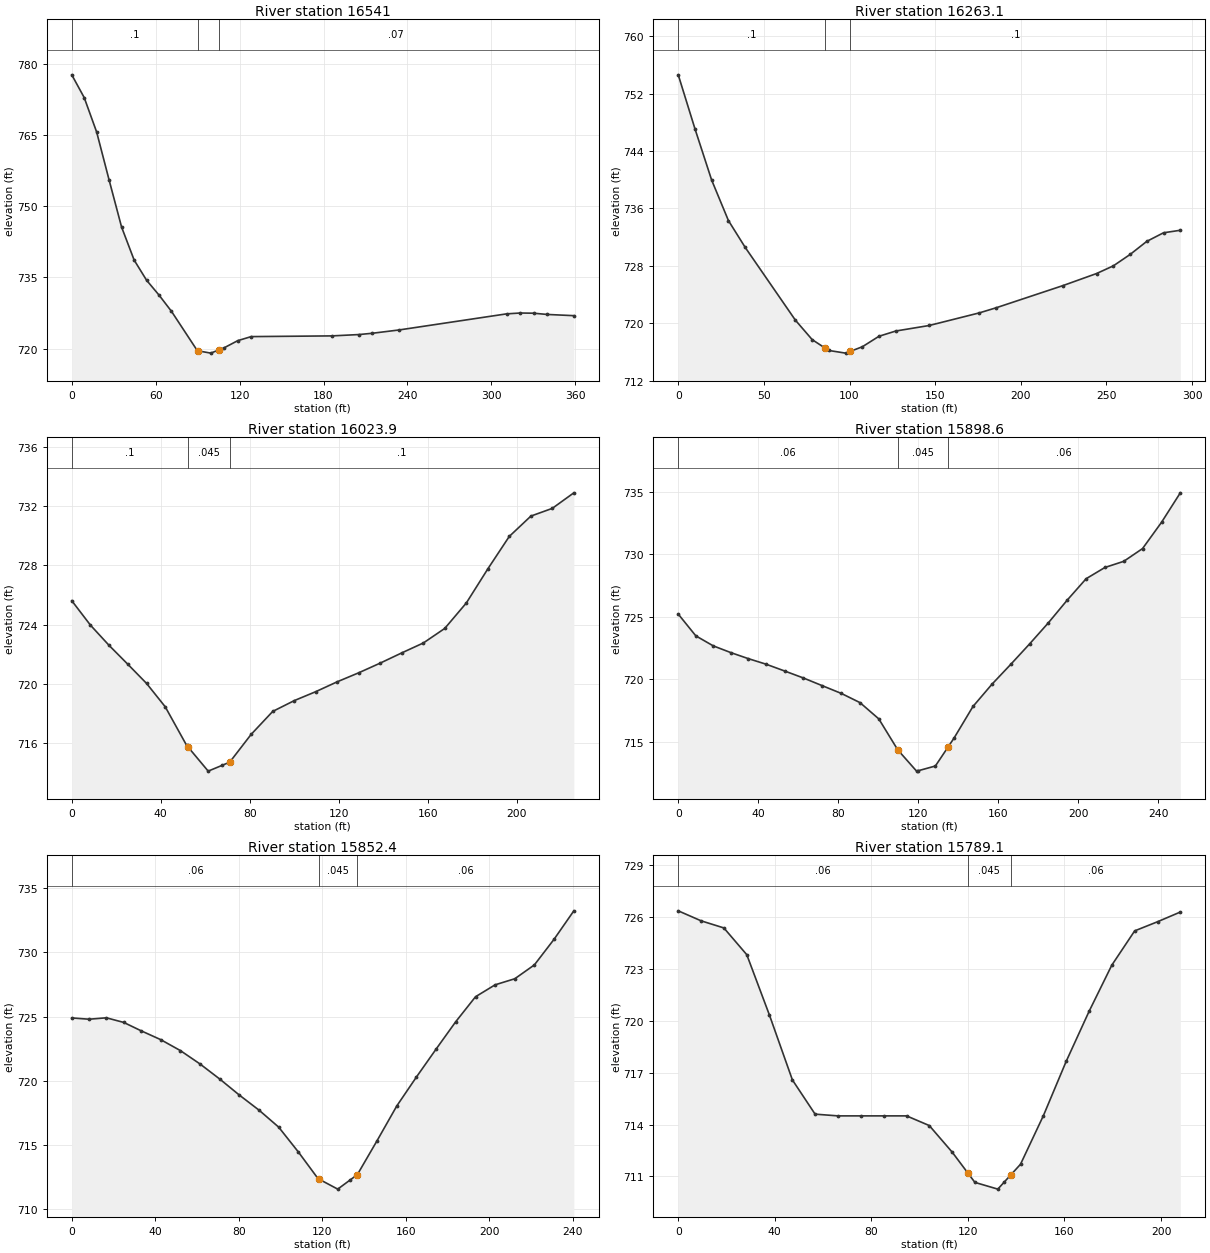
Type RM Length L Ch R = 1 ,16541   ,266.6,277.9,286.5
XS GIS Cut Line= 3
     1819292.015      561100.267     1819371.008      561114.156
     1819601.911      561270.406
#Sta/Elev= 25
       0  777.67     8.9  772.87    17.8  765.61    26.7  755.51    35.6  745.62
    44.6  738.65    53.5   734.4    62.4  731.27    71.3  727.85    89.8  719.56
    90.1  719.54    99.4  719.05   105.1  719.72     109  720.18   118.7  721.68
   128.3  722.53     186  722.68   205.2  722.96   214.8  723.23     234  723.93
   310.9  727.32   320.6   727.5   330.2  727.46   339.8   727.2     359  726.94
#Mann= 3 , 0 , 0
       0      .1       0    90.1    .045       0   105.1     .07       0
Bank Sta=90.1,105.1
XS Rating Curve= 0 ,0
Exp/Cntr=0.3,0.1

Type RM Length L Ch R = 1 ,16263.1 ,240.7,239.2,236.8
XS GIS Cut Line= 2
     1819185.244       561281.69     1819352.779      561522.142
#Sta/Elev= 24
       0  754.62     9.8  747.07    19.5  739.96    29.3  734.31    39.1  730.57
    68.4  720.43    78.2  717.72    85.5  716.58    87.9  716.21    97.7  715.84
   100.5  716.09   107.5  716.73   117.2  718.19     127  718.92   146.5  719.69
   175.8  721.45   185.6  722.16   224.7  725.26   244.2  726.93     254     728
   263.8  729.59   273.5  731.41   283.3  732.61   293.1  732.96
#Mann= 3 , 0 , 0
       0      .1       0    85.5    .045       0   100.5      .1       0
Bank Sta=85.5,100.5
XS Rating Curve= 0 ,0
Exp/Cntr=0.3,0.1

Type RM Length L Ch R = 1 ,16023.9 ,123.5,125.2,127.8
XS GIS Cut Line= 3
     1819033.334       561464.85     1819054.168      561501.308
     1819172.223      561641.933
#Sta/Elev= 27
       0  725.61     8.4  723.96    16.8  722.59    25.2  721.32    33.6  720.03
      42  718.45    51.6  715.85    52.4  715.71    61.3  714.11    67.4  714.49
      71  714.72    80.6  716.59    90.3  718.14     100  718.87   109.6  719.47
   119.3  720.14     129  720.75   138.6   721.4   148.3  722.09     158  722.76
   167.6  723.74   177.3  725.46     187  727.77   196.6  729.95   206.3  731.32
   215.9  731.84   225.6  732.89
#Mann= 3 , 0 , 0
       0      .1       0    52.4    .045       0      71      .1       0
Bank Sta=52.4,71
XS Rating Curve= 0 ,0
Exp/Cntr=0.3,0.1

Type RM Length L Ch R = 1 ,15898.6 ,46,46.2,46
XS GIS Cut Line= 3
     1818939.584      561504.781     1818950.001      561547.315
     1819064.584      561720.058
#Sta/Elev= 30
       0   725.2     8.8  723.46    17.5  722.66    26.3  722.12      35  721.64
    43.8   721.2    53.2  720.65    62.6  720.09    72.1  719.47    81.5  718.86
    90.9  718.12   100.3  716.82   109.8  714.34   119.2  712.64     120  712.67
   128.6  713.05     135  714.58     138   715.3   147.4  717.81   156.9  719.59
   166.3  721.18   175.7  722.81   185.1   724.5   194.6  726.33     204  728.03
   213.4  728.93   222.8  729.42   232.2  730.44   241.7  732.54   251.1   734.9
#Mann= 3 , 0 , 0
       0     .06       0   109.8    .045       0     135     .06       0
Bank Sta=109.8,135
XS Rating Curve= 0 ,0
Exp/Cntr=0.3,0.1

Type RM Length L Ch R = 1 ,15852.4 ,61.8,63.3,64.8
XS GIS Cut Line= 3
     1818884.897      561542.107     1818907.466      561566.413
      1819022.05      561739.156
#Sta/Elev= 29
       0  724.89     8.3  724.79    16.6   724.9    24.9  724.54    33.2  723.89
    42.6   723.2      52  722.35    61.4  721.31    70.9  720.13    80.3  718.88
    89.7  717.71    99.1  716.39   108.6  714.44     118  712.37   118.4  712.34
   127.4  711.56   133.4  712.28   136.8  712.69   146.2  715.32   155.7  718.04
   165.1  720.29   174.5  722.46   183.9  724.59   193.4  726.54   202.8  727.47
   212.2  727.94   221.6  729.02     231  731.01   240.5  733.23
#Mann= 3 , 0 , 0
       0     .06       0   118.4    .045       0   136.8     .06       0
Bank Sta=118.4,136.8
XS Rating Curve= 0 ,0
Exp/Cntr=0.3,0.1

Type RM Length L Ch R = 1 ,15789.1 ,233.6,244.1,254.4
XS GIS Cut Line= 2
     1818842.362      561567.281     1818945.661      561747.836
#Sta/Elev= 26
       0  726.37     9.5  725.79    18.9  725.38    28.4  723.83    37.8  720.33
    47.3  716.58    56.7   714.6    66.2   714.5    75.6   714.5    85.1   714.5
    94.6   714.5     104  713.94   113.5   712.4     120  711.19   122.9  710.65
   132.4  710.26     135  710.66  137.73711.0775   141.8   711.7   151.3  714.52
   160.7  717.65   170.2  720.55   179.6  723.22   189.1  725.21   198.6  725.74
     208   726.3
#Mann= 3 , 0 , 0
       0     .06       0     120    .045       0  137.73     .06       0
Bank Sta=120,137.73
XS Rating Curve= 0 ,0
Exp/Cntr=0.3,0.1

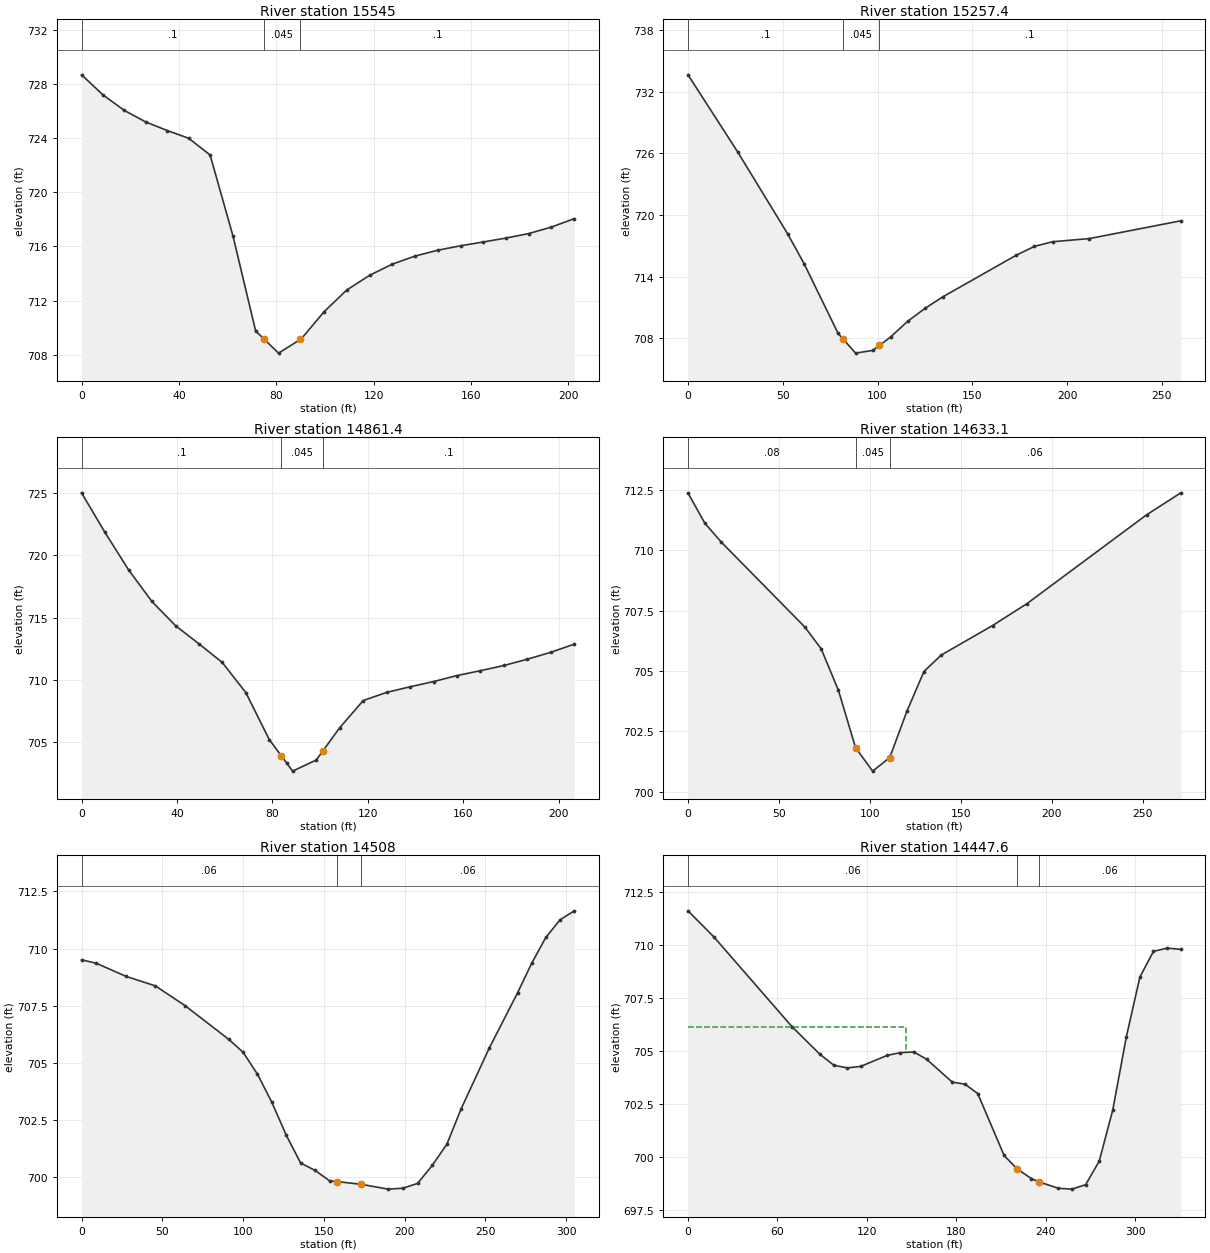
Type RM Length L Ch R = 1 ,15545   ,292.7,287.6,282.8
XS GIS Cut Line= 3
     1818661.807      561641.933     1818674.827      561693.149
     1818683.508      561842.454
#Sta/Elev= 25
       0  728.66     8.8  727.18    17.6  726.03    26.4  725.18    35.2  724.55
      44  723.98    52.8  722.75    62.2  716.77    71.5  709.77    74.9  709.18
    80.9  708.13    89.9  709.14    90.2  709.17    99.6  711.18   108.9  712.78
   118.3  713.87   127.6  714.69     137  715.29   146.3  715.72   155.7  716.05
     165  716.33   174.4  716.62   183.7  716.95     193  717.43   202.4  718.05
#Mann= 3 , 0 , 0
       0      .1       0    74.9    .045       0    89.9      .1       0
Bank Sta=74.9,89.9
XS Rating Curve= 0 ,0
Exp/Cntr=0.3,0.1

Type RM Length L Ch R = 1 ,15257.4 ,388.9,396,402.6
XS GIS Cut Line= 4
     1818413.543      561779.086      1818441.32      561843.322
     1818460.418      561904.954     1818542.883      561999.572
#Sta/Elev= 18
       0  733.66    26.2  726.15    52.5  718.19    61.2  715.28    79.2  708.47
      82  707.89    88.4  706.55    97.6  706.82  100.97707.2947   106.9  708.13
   116.1  709.68   125.3  710.94   134.5  712.04   173.1  716.08   182.8  716.95
   192.4   717.4   211.8  717.71     260  719.44
#Mann= 3 , 0 , 0
       0      .1       0      82    .045       0  100.97      .1       0
Bank Sta=82,100.97
XS Rating Curve= 0 ,0
Exp/Cntr=0.3,0.1

Type RM Length L Ch R = 1 ,14861.4 ,242.4,228.3,214.2
XS GIS Cut Line= 2
     1818107.119      561920.579     1818105.383      562127.177
#Sta/Elev= 25
       0     725     9.8  721.83    19.7  718.83    29.5  716.29    39.4  714.35
    49.2   712.9      59   711.4    68.9  708.98    78.7  705.22    83.7703.9294
    86.1  703.31    88.5  702.69    98.4  703.58   101.1  704.29   108.2  706.16
   118.1  708.35   127.9     709   137.7  709.45   147.6  709.87   157.4  710.35
   167.2  710.74   177.1  711.16   186.9  711.66   196.8  712.22   206.6  712.87
#Mann= 3 , 0 , 0
       0      .1       0    83.7    .045       0   101.1      .1       0
Bank Sta=83.7,101.1
XS Rating Curve= 0 ,0
Exp/Cntr=0.3,0.1

Type RM Length L Ch R = 1 ,14633.1 ,101.6,125.1,144.9
XS GIS Cut Line= 3
     1817871.008      561965.718     1817877.952      562038.635
       1817990.8      562200.961
#Sta/Elev= 16
       0  712.36     9.2  711.12    18.3  710.33    64.1  706.83    73.2  705.92
    82.7   704.2    92.1  701.83   101.5  700.86   110.9  701.42   120.3  703.33
   129.7  704.98   139.2  705.66   167.4  706.88   186.2  707.78   252.1  711.46
   270.9  712.37
#Mann= 3 , 0 , 0
       0     .08       0    92.1    .045       0   110.9     .06       0
Bank Sta=92.1,110.9
XS Rating Curve= 0 ,0
Exp/Cntr=0.3,0.1

Type RM Length L Ch R = 1 ,14508   ,83.8,60.4,62.2
XS GIS Cut Line= 5
     1817739.932       562027.35     1817797.223      562086.378
     1817828.473      562140.197     1817875.348      562207.038
     1817944.793      562244.364
#Sta/Elev= 27
       0  709.51     9.1  709.36    27.4  708.79    45.7  708.37      64  707.51
    91.2  706.03     100  705.47   108.9  704.51   117.8  703.28   126.7  701.85
   135.6  700.63   144.5  700.31   153.6  699.85   158.1  699.82   173.1   699.7
   189.8  699.49   198.9  699.53     208  699.74   217.1  700.53   226.1  701.45
   234.9  702.99   252.4  705.66   269.9  708.07   278.7  709.37   287.4  710.49
   296.2  711.26     305  711.65
#Mann= 3 , 0 , 0
       0     .06       0   158.1    .045       0   173.1     .06       0
Bank Sta=158.1,173.1
XS Rating Curve= 0 ,0
Exp/Cntr=0.3,0.1

Type RM Length L Ch R = 1 ,14447.6 ,89.1,93.6,75.6
XS GIS Cut Line= 6
     1817665.279      562086.378     1817735.591      562154.086
     1817778.994      562185.336     1817829.306      562196.417
     1817856.251      562233.079     1817871.008      562313.808
#Sta/Elev= 28
       0  711.63    17.2  710.41    69.8  706.16    88.5  704.86    97.9  704.34
   106.8  704.22   115.8  704.29   133.6  704.81   142.5  704.94   151.4  704.97
     160  704.63   177.2  703.55   185.8  703.45   194.3  703.01     212  700.09
   220.5  699.47   230.2     699   235.5  698.84   248.4  698.54   257.5   698.5
   266.7  698.71   275.8  699.82   284.9  702.24     294  705.69   303.1  708.51
   312.2  709.72   321.4  709.87   330.5  709.81
#Mann= 3 , 0 , 0
       0     .06       0   220.5    .045       0   235.5     .06       0
#XS Ineff= 2 , 0
          146.47  706.16
Permanent Ineff=
       F       F
Bank Sta=220.5,235.5
XS Rating Curve= 0 ,0
Exp/Cntr=0.3,0.1

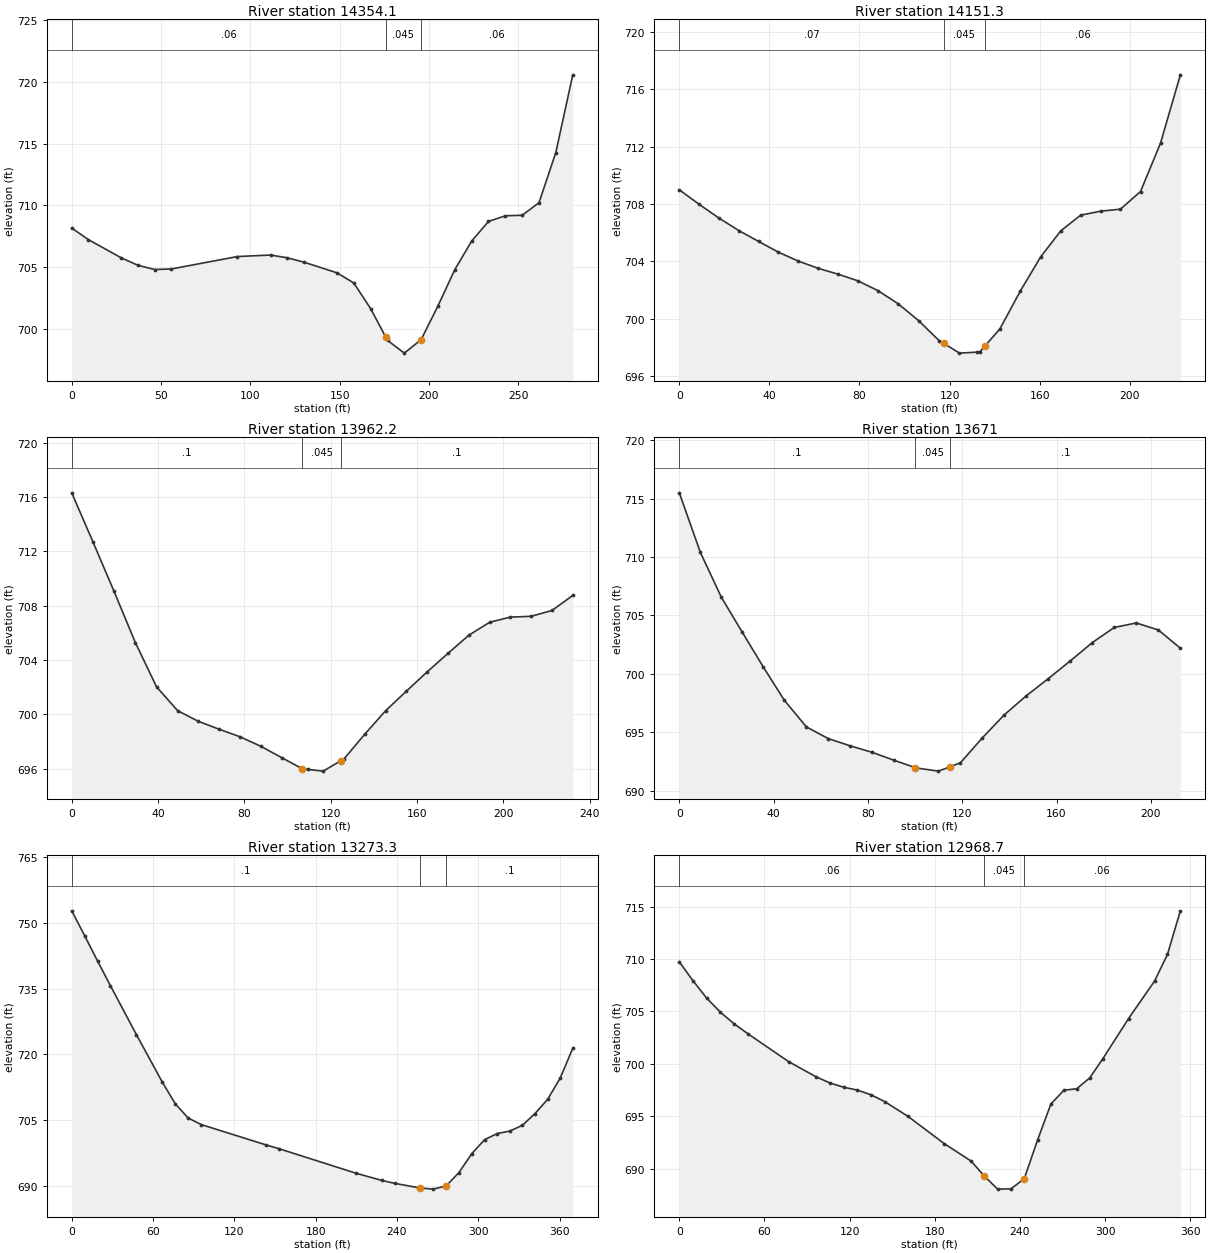
Type RM Length L Ch R = 1 ,14354.1 ,198.4,202.8,207.1
XS GIS Cut Line= 3
     1817647.918       562179.26     1817777.258      562252.177
      1817834.55        562371.1
#Sta/Elev= 26
       0  708.17     9.3  707.23    27.8  705.75    37.1  705.15    46.4  704.81
    55.7  704.85    92.8  705.86   111.4  705.98   120.6  705.76   129.9  705.41
   148.5  704.54   157.9  703.72   167.3  701.65   175.8  699.34   176.8  699.07
   186.2  698.04   195.6  699.13     205  701.85   214.5  704.81   223.9  707.11
   233.3   708.7   242.8  709.16   252.2   709.2   261.6  710.22     271  714.27
   280.5  720.57
#Mann= 3 , 0 , 0
       0     .06       0   175.8    .045       0   195.6     .06       0
Bank Sta=175.8,195.6
XS Rating Curve= 0 ,0
Exp/Cntr=0.3,0.1

Type RM Length L Ch R = 1 ,14151.3 ,204.7,189.1,173.4
XS GIS Cut Line= 4
     1817569.793      562302.524     1817625.348      562358.947
     1817647.918      562437.072     1817693.057      562479.607
#Sta/Elev= 29
       0  708.99     8.8  707.98    17.6  707.02    26.4  706.15    35.2  705.39
      44  704.64    52.8  704.02    61.6  703.52    70.4  703.11    79.2  702.65
    88.2  701.96    97.2  701.04   106.3  699.86   115.3  698.48   117.4  698.28
   124.4   697.6   132.4  697.67   133.4  697.68  135.74698.1012   142.4   699.3
   151.5  701.95   160.5  704.32   169.4  706.13   178.2  707.22   187.1   707.5
   195.9  707.64   204.8  708.87   213.7  712.25   222.5  717.01
#Mann= 3 , 0 , 0
       0     .07       0   117.4    .045       0  135.74     .06       0
Bank Sta=117.4,135.74
XS Rating Curve= 0 ,0
Exp/Cntr=0.3,0.1

Type RM Length L Ch R = 1 ,13962.2 ,285.2,291.2,297.1
XS GIS Cut Line= 3
     1817390.105      562420.579     1817424.827      562455.302
     1817575.869        562558.6
#Sta/Elev= 27
       0  716.32     9.8  712.72    19.6  709.06    29.5  705.28    39.3  702.02
    49.1  700.26    58.7  699.48    68.4  698.89      78  698.34    87.6  697.64
    97.3   696.8   106.9  695.98   109.6  695.93   116.5  695.81   124.6  696.57
   126.2  696.72   135.8  698.54   145.4  700.26     155   701.7   164.7  703.13
   174.3  704.49   183.9  705.82   193.6  706.78   203.2  707.16   212.8  707.22
   222.5  707.65   232.1  708.76
#Mann= 3 , 0 , 0
       0      .1       0   106.9    .045       0   124.6      .1       0
Bank Sta=106.9,124.6
XS Rating Curve= 0 ,0
Exp/Cntr=0.3,0.1

Type RM Length L Ch R = 1 ,13671   ,406.8,397.7,388.3
XS GIS Cut Line= 3
      1817191.32      562582.906     1817215.626      562620.232
     1817325.869      562746.968
#Sta/Elev= 26
       0  715.49     8.9  710.41    17.8  706.57    26.7  703.57    35.6   700.6
    44.5  697.76    53.9  695.47    63.2  694.47    72.5  693.85    81.9  693.29
    91.2  692.61    99.9     692   100.5  691.96   109.9  691.69   114.9  692.07
   119.2   692.4   128.5  694.53   137.9  696.52   147.2  698.14   156.5   699.6
   165.9  701.13   175.2  702.69   184.5  703.98   193.8  704.36   203.2  703.76
   212.5   702.2
#Mann= 3 , 0 , 0
       0      .1       0    99.9    .045       0   114.9      .1       0
Bank Sta=99.9,114.9
XS Rating Curve= 0 ,0
Exp/Cntr=0.3,0.1

Type RM Length L Ch R = 1 ,13273.3 ,311.1,304.6,297.7
XS GIS Cut Line= 4
     1816771.182      562819.017     1816931.772      562922.315
     1817034.202      562971.795     1817088.022      563008.253
#Sta/Elev= 27
       0  752.77     9.6  747.05    19.1  741.28    28.6  735.64    47.7   724.5
    66.8  713.65    76.4  708.69    85.9  705.43    95.5  703.94   143.2   699.3
   152.8  698.43   209.9   692.8   228.9  691.16   238.3   690.5   256.9  689.45
   266.8  689.18   276.3  689.92   285.7  692.96   295.2  697.29   304.7   700.5
     314  701.88   323.3  702.45   332.6  703.78   341.8  706.44   351.1  709.67
   360.4  714.54   369.7  721.35
#Mann= 3 , 0 , 0
       0      .1       0   256.9    .045       0   276.3      .1       0
Bank Sta=256.9,276.3
XS Rating Curve= 0 ,0
Exp/Cntr=0.3,0.1

Type RM Length L Ch R = 1 ,12968.7 ,112.6,108.2,99.7
XS GIS Cut Line= 5
      1816686.98      563131.517     1816805.904      563213.982
     1816836.286      563226.135     1816919.619      563239.156
     1817009.897      563252.177
#Sta/Elev= 30
       0  709.74     9.6  707.94    19.3  706.27    28.9  704.93    38.6  703.82
    48.2  702.88    77.2  700.19    96.5  698.75   106.1  698.17   115.8  697.76
   125.4  697.49   135.1  697.04   144.7  696.39   161.1  694.98   186.8  692.36
   205.6  690.71   214.9  689.27   224.3  688.03   233.7  688.06     243  689.02
   252.4  692.72   261.8  696.16   270.9  697.47     280  697.62   289.2  698.66
   298.3  700.47   316.5  704.32   334.8   707.9   343.9  710.44     353  714.61
#Mann= 3 , 0 , 0
       0     .06       0   214.9    .045       0     243     .06       0
Bank Sta=214.9,243
XS Rating Curve= 0 ,0
Exp/Cntr=0.3,0.1

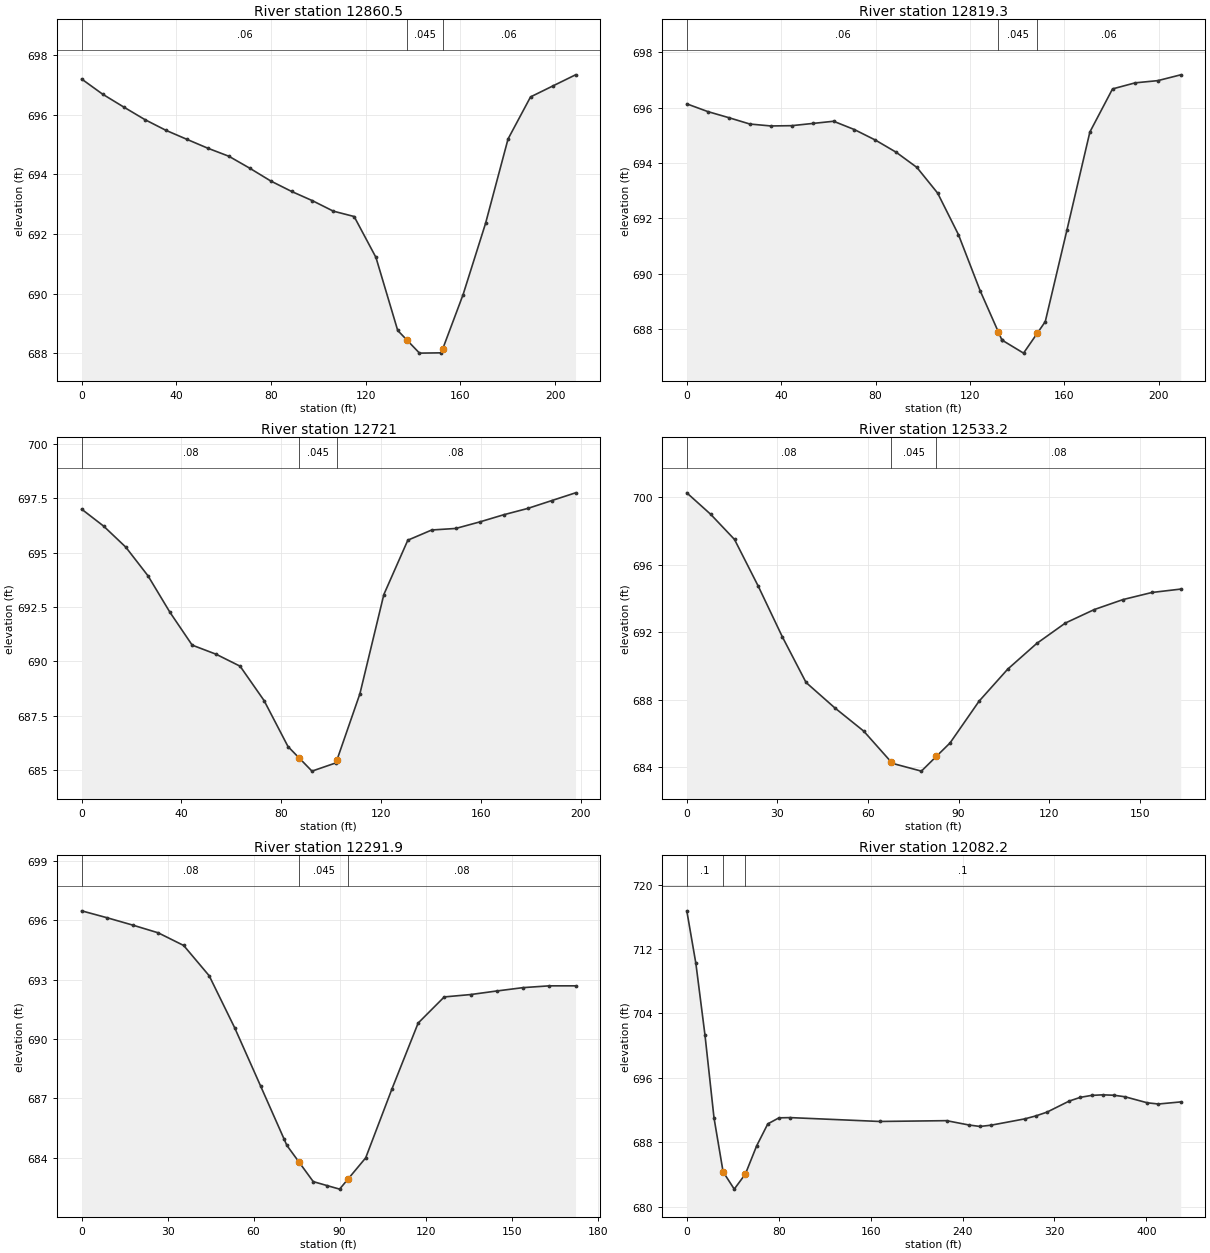
Type RM Length L Ch R = 1 ,12860.5 ,41.1,41.1,45.8
XS GIS Cut Line= 5
     1816768.577      563258.253     1816792.883      563315.545
      1816838.89      563341.586     1816884.897       563339.85
     1816923.959       563312.94
#Sta/Elev= 26
       0   697.2     8.9  696.69    17.8  696.26    26.7  695.84    35.6  695.48
    44.4  695.18    53.3  694.88    62.2  694.61      71  694.21    79.9  693.78
    88.7  693.43    97.5  693.12   106.3  692.77   115.1  692.59   124.3  691.22
   133.5  688.77   137.5  688.44   142.7  688.01   151.9  688.02   152.5  688.15
   161.1  689.97   170.6  692.36   180.1  695.19   189.6   696.6   199.1  696.97
   208.6  697.34
#Mann= 3 , 0 , 0
       0     .06       0   137.5    .045       0   152.5     .06       0
Bank Sta=137.5,152.5
XS Rating Curve= 0 ,0
Exp/Cntr=0.3,0.1

Type RM Length L Ch R = 1 ,12819.3 ,97.9,98.4,98.4
XS GIS Cut Line= 5
     1816768.577      563299.052     1816792.883      563356.343
      1816838.89      563382.385     1816884.897      563380.649
      1816932.64      563386.725
#Sta/Elev= 27
       0  696.14     8.9  695.86    17.8  695.64    26.7  695.41    35.6  695.34
    44.4  695.35    53.3  695.43    62.2  695.51      71  695.21    79.9  694.83
    88.7  694.39    97.5  693.84   106.3  692.91   115.1  691.41   124.3  689.38
  131.98 687.894   133.5   687.6   133.6  687.59   142.7  687.12   148.6  687.85
   151.9  688.26   161.1  691.58   170.8  695.12   180.4  696.68     190   696.9
   199.6  696.98   209.3  697.19
#Mann= 3 , 0 , 0
       0     .06       0  131.98    .045       0   148.6     .06       0
Bank Sta=131.98,148.6
XS Rating Curve= 0 ,0
Exp/Cntr=0.3,0.1

Type RM Length L Ch R = 1 ,12721   ,186.9,187.7,188.3
XS GIS Cut Line= 3
     1816770.314      563461.378     1816810.244      563480.475
      1816963.89      563477.871
#Sta/Elev= 24
       0  697.01     8.8  696.23    17.7  695.26    26.6  693.94    35.4  692.26
    44.3  690.75    53.9  690.33    63.5  689.78    73.1   688.2    82.7  686.08
    87.3  685.54    92.3  684.95   101.9  685.33   102.3  685.46   111.5  688.51
   121.1  693.08   130.7  695.58   140.3  696.05   149.9  696.12   159.5  696.42
   169.1  696.75   178.7  697.04   188.3   697.4   197.9  697.76
#Mann= 3 , 0 , 0
       0     .08       0    87.3    .045       0   102.3     .08       0
Bank Sta=87.3,102.3
XS Rating Curve= 0 ,0
Exp/Cntr=0.3,0.1

Type RM Length L Ch R = 1 ,12533.2 ,241.8,241.3,240.8
XS GIS Cut Line= 3
     1816738.195      563634.989     1816771.182       563656.69
     1816895.314      563658.427
#Sta/Elev= 21
       0  700.26     7.9  698.99    15.8   697.5    23.7  694.72    31.6  691.75
    39.5  689.03      49  687.53    58.6  686.15    67.7  684.32    68.1  684.24
    77.7  683.78    82.7  684.66    87.2  685.45    96.8  687.92   106.3  689.82
   115.9  691.34   125.4  692.55     135  693.35   144.5  693.94   154.1  694.36
   163.6  694.56
#Mann= 3 , 0 , 0
       0     .08       0    67.7    .045       0    82.7     .08       0
Bank Sta=67.7,82.7
XS Rating Curve= 0 ,0
Exp/Cntr=0.3,0.1

Type RM Length L Ch R = 1 ,12291.9 ,201.3,209.7,220.9
XS GIS Cut Line= 3
     1816739.932      563877.177     1816789.411      563897.142
     1816908.334      563896.274
#Sta/Elev= 24
       0  696.48     8.9  696.13    17.8  695.76    26.7  695.37    35.6  694.73
    44.5   693.2    53.4  690.57    62.5  687.61    70.6  684.96    71.6  684.63
   75.89683.7767    80.8   682.8    85.6   682.6      90  682.42   92.95682.9322
    99.1     684   108.2  687.46   117.4  690.81   126.5  692.13   135.7  692.25
   144.8  692.43     154   692.6   163.1  692.69   172.3  692.69
#Mann= 3 , 0 , 0
       0     .08       0   75.89    .045       0   92.95     .08       0
Bank Sta=75.89,92.95
XS Rating Curve= 0 ,0
Exp/Cntr=0.3,0.1

Type RM Length L Ch R = 1 ,12082.2 ,155,163.2,166.6
XS GIS Cut Line= 4
     1816706.077      564080.302     1816736.459      564088.982
     1816908.334      564180.128     1817025.522      564346.795
#Sta/Elev= 29
       0  716.76     7.9  710.22    15.8  701.35    23.7  691.01    31.6  684.32
    31.7   684.3    41.3  682.17      51  684.05    60.8  687.55    70.5  690.28
    80.2  691.03      90  691.06   167.8  690.58   226.1  690.68   245.6  690.14
   255.2  689.96     265  690.12   294.1   690.9   303.8  691.27   313.5  691.74
   332.9  693.12   342.6  693.58   352.3  693.82     362  693.89   371.7  693.84
   381.4  693.65   400.8   692.9   410.5  692.75   429.9  693.01
#Mann= 3 , 0 , 0
       0      .1       0    31.7    .045       0      51      .1       0
Bank Sta=31.7,51
XS Rating Curve= 0 ,0
Exp/Cntr=0.3,0.1

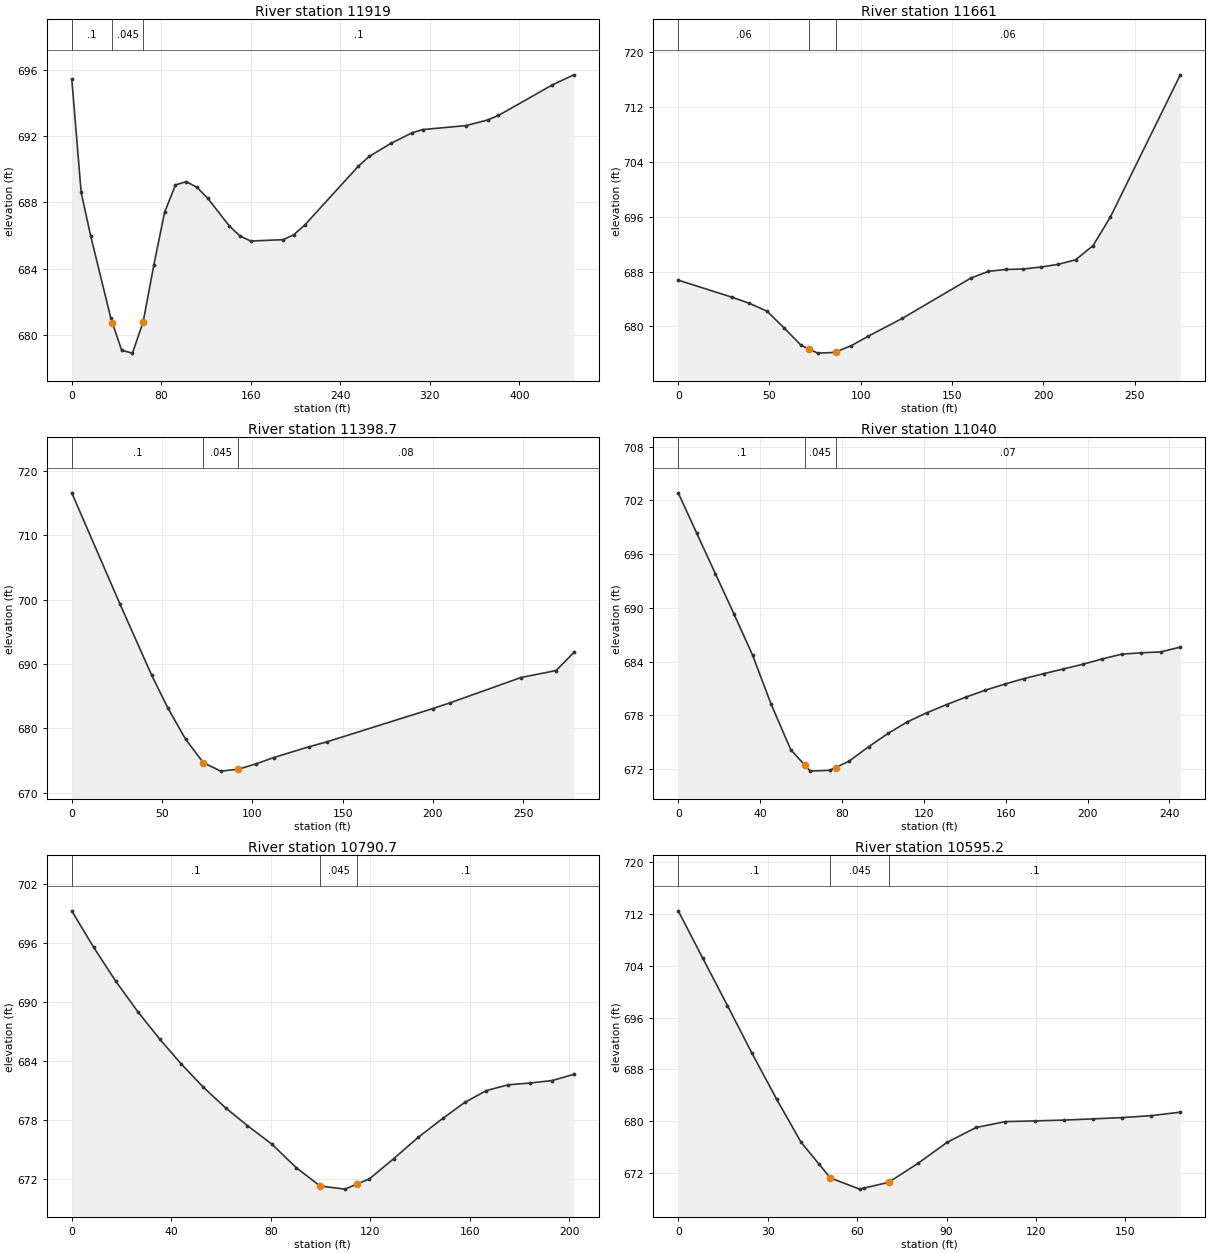
Type RM Length L Ch R = 1 ,11919   ,247.7,258.1,270
XS GIS Cut Line= 3
     1816626.216      564195.753     1816639.237      564217.454
     1816977.779      564471.795
#Sta/Elev= 30
       0  695.44     8.4   688.6    16.9  685.98    34.9  681.02    36.3  680.74
    44.6  679.08    54.2  678.91    63.8  680.79    73.4  684.23      83  687.41
    92.7  689.05   102.3  689.25   111.9  688.91   121.5  688.25   140.8  686.58
   150.4  685.97     160  685.67   188.9  685.75   198.5  686.05   208.2  686.63
   256.3  690.19   265.9  690.77   285.1  691.55   304.4   692.2     314  692.39
   352.5  692.63   371.8  692.97   381.4  693.24   429.5  695.08   448.8  695.69
#Mann= 3 , 0 , 0
       0      .1       0    36.3    .045       0    63.8      .1       0
Bank Sta=36.3,63.8
XS Rating Curve= 0 ,0
Exp/Cntr=0.3,0.1

Type RM Length L Ch R = 1 ,11661   ,263.3,262.3,261
XS GIS Cut Line= 4
     1816429.168      564303.392     1816442.189      564350.267
     1816478.647      564435.336     1816509.897      564565.545
#Sta/Elev= 23
       0  686.75    29.2  684.28    38.9  683.38    48.6  682.23    57.9  679.82
    67.2  677.28    71.5  676.73    76.4  676.11    85.7  676.21    86.5   676.3
    94.9  677.21   104.2  678.59   122.7  681.16   160.3  687.04   169.9  688.03
   179.5   688.3     189  688.37   198.6  688.65   208.2  689.05   217.7  689.71
   227.3  691.78   236.8  695.96   275.1  716.67
#Mann= 3 , 0 , 0
       0     .06       0    71.5    .045       0    86.5     .06       0
Bank Sta=71.5,86.5
XS Rating Curve= 0 ,0
Exp/Cntr=0.3,0.1

Type RM Length L Ch R = 1 ,11398.7 ,364.7,358.7,352.7
XS GIS Cut Line= 3
     1816180.036      564345.927     1816185.244      564398.878
     1816283.334      564601.135
#Sta/Elev= 17
       0  716.63    26.6   699.4    44.3  688.25    53.2  683.19      63  678.35
    72.8  674.69    82.5  673.37    92.3  673.67   102.1  674.51   111.8  675.48
   131.4  677.16   141.2  677.92   199.8  683.09   209.6     684   248.7  687.92
   268.2  689.01     278  691.82
#Mann= 3 , 0 , 0
       0      .1       0    72.8    .045       0    92.3     .08       0
Bank Sta=72.8,92.3
XS Rating Curve= 0 ,0
Exp/Cntr=0.3,0.1

Type RM Length L Ch R = 1 ,11040   ,244.6,249.3,254.3
XS GIS Cut Line= 3
     1815857.987      564564.677     1815890.973      564595.927
     1816023.786      564745.232
#Sta/Elev= 29
       0  702.85     9.1  698.31    18.2   693.8    27.3  689.29    36.4  684.69
    45.4  679.24      55  674.17    61.9  672.43    64.5  671.78      74  671.87
    76.9  672.18    83.5   672.9      93   674.5   102.5  675.99     112  677.29
   121.6  678.31   131.1  679.21   140.6  680.05   150.1  680.82   159.6   681.5
   169.1  682.12   178.7  682.67   188.2  683.19   197.7  683.71   207.2  684.31
   216.7  684.84   226.2  684.99   235.8  685.09   245.3  685.63
#Mann= 3 , 0 , 0
       0      .1       0    61.9    .045       0    76.9     .07       0
Bank Sta=61.9,76.9
XS Rating Curve= 0 ,0
Exp/Cntr=0.3,0.1

Type RM Length L Ch R = 1 ,10790.7 ,197,195.5,193.3
XS GIS Cut Line= 4
     1815665.279      564726.135     1815725.175      564763.461
     1815763.369      564832.038     1815781.598      564881.517
#Sta/Elev= 24
       0  699.32     8.8  695.61    17.6  692.19    26.5  689.08    35.3  686.29
    44.1  683.72    52.9  681.38    61.8  679.29    70.6  677.48    80.4   675.6
    90.2  673.21    99.8  671.34   109.8  671.02   114.8  671.55   119.6  672.06
   129.4  674.12   139.3   676.3   149.1  678.21   157.9  679.83   166.6  681.04
   175.4  681.63   184.2  681.81     193  682.06   201.8  682.69
#Mann= 3 , 0 , 0
       0      .1       0    99.8    .045       0   114.8      .1       0
Bank Sta=99.8,114.8
XS Rating Curve= 0 ,0
Exp/Cntr=0.3,0.1

Type RM Length L Ch R = 1 ,10595.2 ,250.2,252.2,254.8
XS GIS Cut Line= 3
     1815556.772      564850.267     1815577.605      564885.857
     1815650.522      564990.024
#Sta/Elev= 21
       0  712.51     8.2  705.21    16.5  697.87    24.7  690.52      33  683.39
    41.2  676.73    47.2  673.36      51  671.22    60.8  669.48    62.2  669.63
    70.6  670.54    80.4  673.46    90.1  676.69    99.9  679.01   109.7  679.92
   119.5  680.03   129.3  680.15     139  680.34   148.8  680.54   158.6  680.84
   168.4  681.38
#Mann= 3 , 0 , 0
       0      .1       0      51    .045       0    70.6      .1       0
Bank Sta=51,70.6
XS Rating Curve= 0 ,0
Exp/Cntr=0.3,0.1

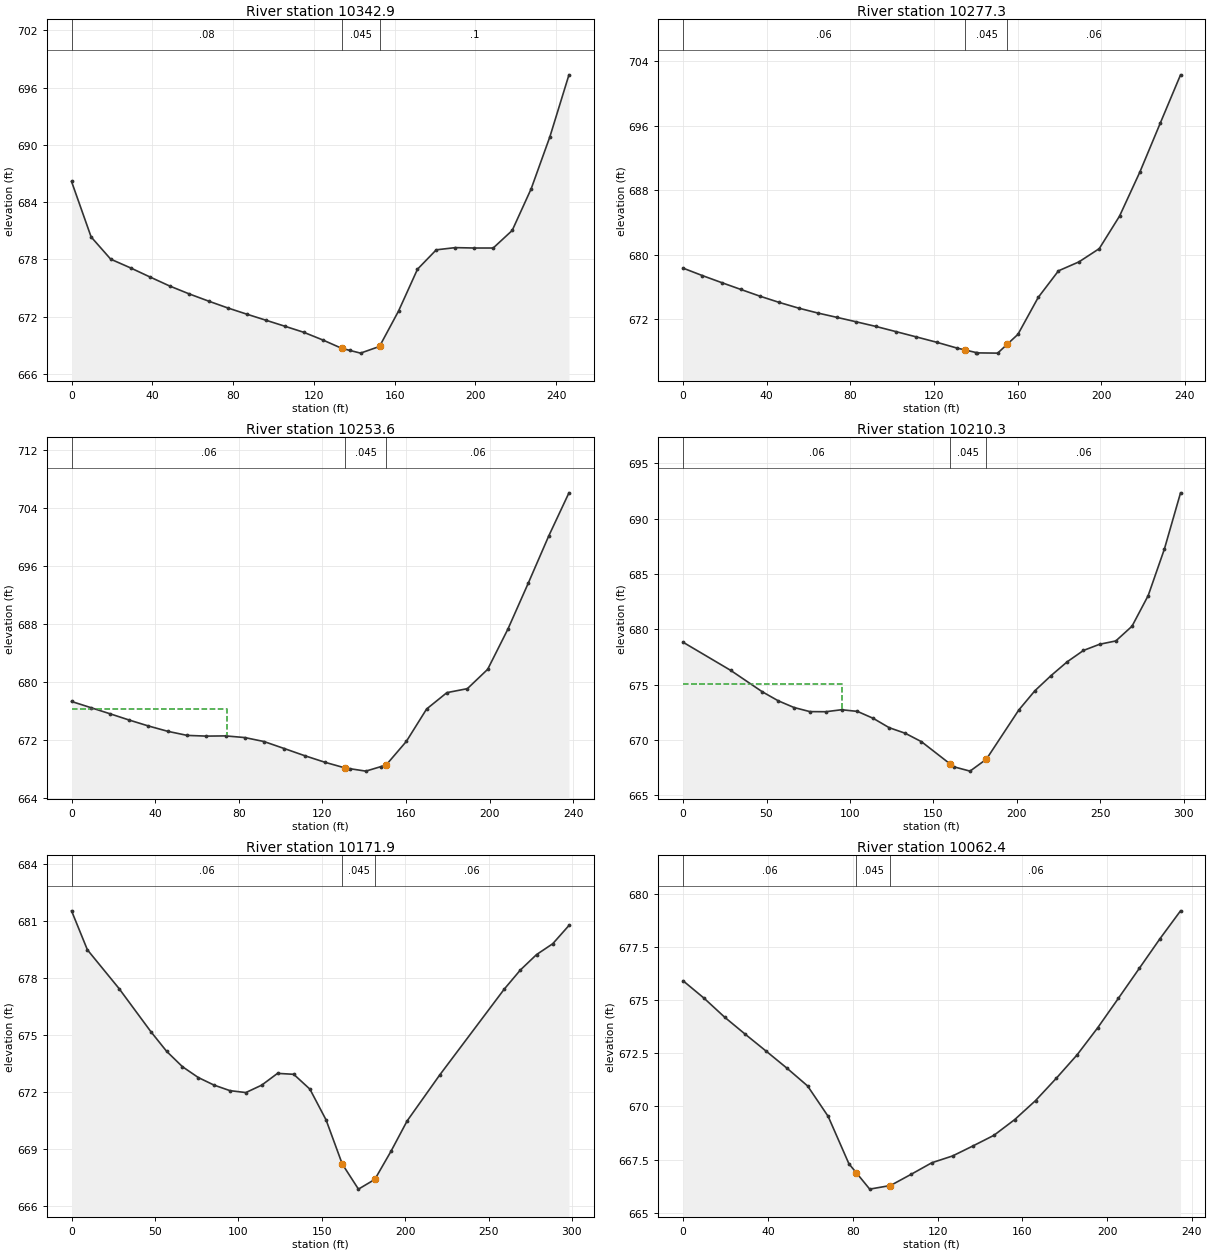
Type RM Length L Ch R = 1 ,10342.9 ,62.8,65.6,68.5
XS GIS Cut Line= 3
     1815331.077      564897.142     1815338.022       564964.85
     1815422.223      565121.968
#Sta/Elev= 29
       0  686.16     9.7  680.35    19.4  678.02    29.2  677.11    38.9  676.15
    48.6  675.21    58.3  674.38    68.1  673.61    77.4  672.91    86.8  672.26
    96.2  671.63   105.6     671     115  670.36   124.4  669.56   133.7  668.69
   137.7  668.47   143.1  668.18   152.5  668.88   152.7  668.96   161.9  672.58
   171.3  676.97   180.6     679     190  679.23   199.4  679.19   208.8  679.19
   218.2  681.03   227.6   685.4   236.9  690.87   246.3  697.33
#Mann= 3 , 0 , 0
       0     .08       0   133.7    .045       0   152.7      .1       0
Bank Sta=133.7,152.7
XS Rating Curve= 0 ,0
Exp/Cntr=0.3,0.1

Type RM Length L Ch R = 1 ,10277.3 ,23.6,23.6,23.6
XS GIS Cut Line= 3
     1815292.883      564920.579     1815297.223      565012.593
     1815349.307      565148.878
#Sta/Elev= 29
       0  678.34     9.2  677.42    18.4  676.55    27.6   675.7    36.8  674.86
    46.1  674.08    55.3  673.38    64.5  672.77    73.7  672.23    82.9  671.68
    92.1  671.12   101.8  670.47   111.6  669.81   121.3  669.15     131  668.43
  135.08668.1816   140.2  667.87   140.8  667.83   150.5   667.8   155.2  668.93
   160.2  670.13   169.9  674.71   179.6  678.01   189.4  679.12   199.1  680.76
   208.8  684.79   218.6   690.3   228.3  696.33     238  702.32
#Mann= 3 , 0 , 0
       0     .06       0  135.08    .045       0   155.2     .06       0
Bank Sta=135.08,155.2
XS Rating Curve= 0 ,0
Exp/Cntr=0.3,0.1

Type RM Length L Ch R = 1 ,10253.6 ,22.9,43.3,63.8
XS GIS Cut Line= 3
     1815272.918      564934.468     1815277.258      565026.482
     1815329.341      565162.767
#Sta/Elev= 28
       0  677.29     9.2  676.44    18.4  675.59    27.6  674.72    36.8   673.9
    46.1  673.16    55.3   672.6    64.5   672.5    73.7  672.53    82.9   672.3
    92.1  671.75   101.8  670.78   111.6  669.79   121.3  668.88     131  668.09
   133.1     668   140.8  667.66   148.1  668.29   150.5   668.5   160.2  671.77
   169.9  676.25   179.6  678.51   189.4  679.06   199.1  681.73   208.8   687.3
   218.6  693.69   228.3  700.15     238  706.13
#Mann= 3 , 0 , 0
       0     .06       0     131    .045       0   150.5     .06       0
#XS Ineff= 2 , 0
           74.18   676.3
Permanent Ineff=
       F       F
Bank Sta=131,150.5
XS Rating Curve= 0 ,0
Exp/Cntr=0.3,0.1

Type RM Length L Ch R = 1 ,10210.3 ,38.8,38.4,36.8
XS GIS Cut Line= 3
     1815263.369      564918.843     1815271.182      565042.107
     1815196.529      565200.093
#Sta/Elev= 28
       0  678.82    28.5  676.28    47.5  674.34      57  673.53    66.5  672.92
      76  672.55    85.5  672.54      95  672.72   104.5  672.57     114  671.94
   123.5   671.1   133.2  670.59   142.9  669.83   159.8  667.85   162.3  667.56
     172  667.17   181.8  668.25   201.2  672.69   210.9  674.44   220.6  675.81
   230.3  677.06     240  678.08   249.7  678.64   259.4  678.94   269.1  680.27
   278.8  683.04   288.5  687.24   298.2  692.33
#Mann= 3 , 0 , 0
       0     .06       0   159.8    .045       0   181.8     .06       0
#XS Ineff= 2 , 0
           95.05  675.03
Permanent Ineff=
       F       F
Bank Sta=159.8,181.8
XS Rating Curve= 0 ,0
Exp/Cntr=0.3,0.1

Type RM Length L Ch R = 1 ,10171.9 ,120.8,109.6,98.7
XS GIS Cut Line= 3
     1815231.251      564908.427     1815239.064       565031.69
     1815164.411      565189.677
#Sta/Elev= 26
       0  681.55     9.5   679.5    28.5  677.46    47.5   675.2      57  674.16
    66.5  673.35      76  672.78    85.5  672.38      95  672.09   104.5  671.99
     114  672.38   123.5     673   133.2  672.95   142.9  672.17   152.6  670.55
   162.3  668.23     172  666.91   181.8  667.42   191.5   668.9   201.2   670.5
   220.6   672.9   259.4  677.43   269.1  678.44   278.8  679.25   288.5  679.82
   298.2  680.78
#Mann= 3 , 0 , 0
       0     .06       0   162.3    .045       0   181.8     .06       0
Bank Sta=162.3,181.8
XS Rating Curve= 0 ,0
Exp/Cntr=0.3,0.1

Type RM Length L Ch R = 1 ,10062.4 ,100.6,100.9,101.5
XS GIS Cut Line= 2
     1815117.536      564940.545      1815128.82       565174.92
#Sta/Elev= 27
       0   675.9     9.8  675.09    19.6  674.19    29.3  673.39    39.1   672.6
    48.9   671.8    58.7  670.96    68.4  669.53    78.2   667.3    81.6  666.89
      88  666.11    96.6  666.26    97.8  666.28   107.6  666.81   117.3  667.35
   127.1  667.67   136.9  668.15   146.6  668.64   156.4  669.38   166.2  670.27
     176  671.32   185.8  672.42   195.5  673.69   205.3  675.08   215.1  676.48
   224.9  677.88   234.6  679.19
#Mann= 3 , 0 , 0
       0     .06       0    81.6    .045       0    97.8     .06       0
Bank Sta=81.6,97.8
XS Rating Curve= 0 ,0
Exp/Cntr=0.3,0.1