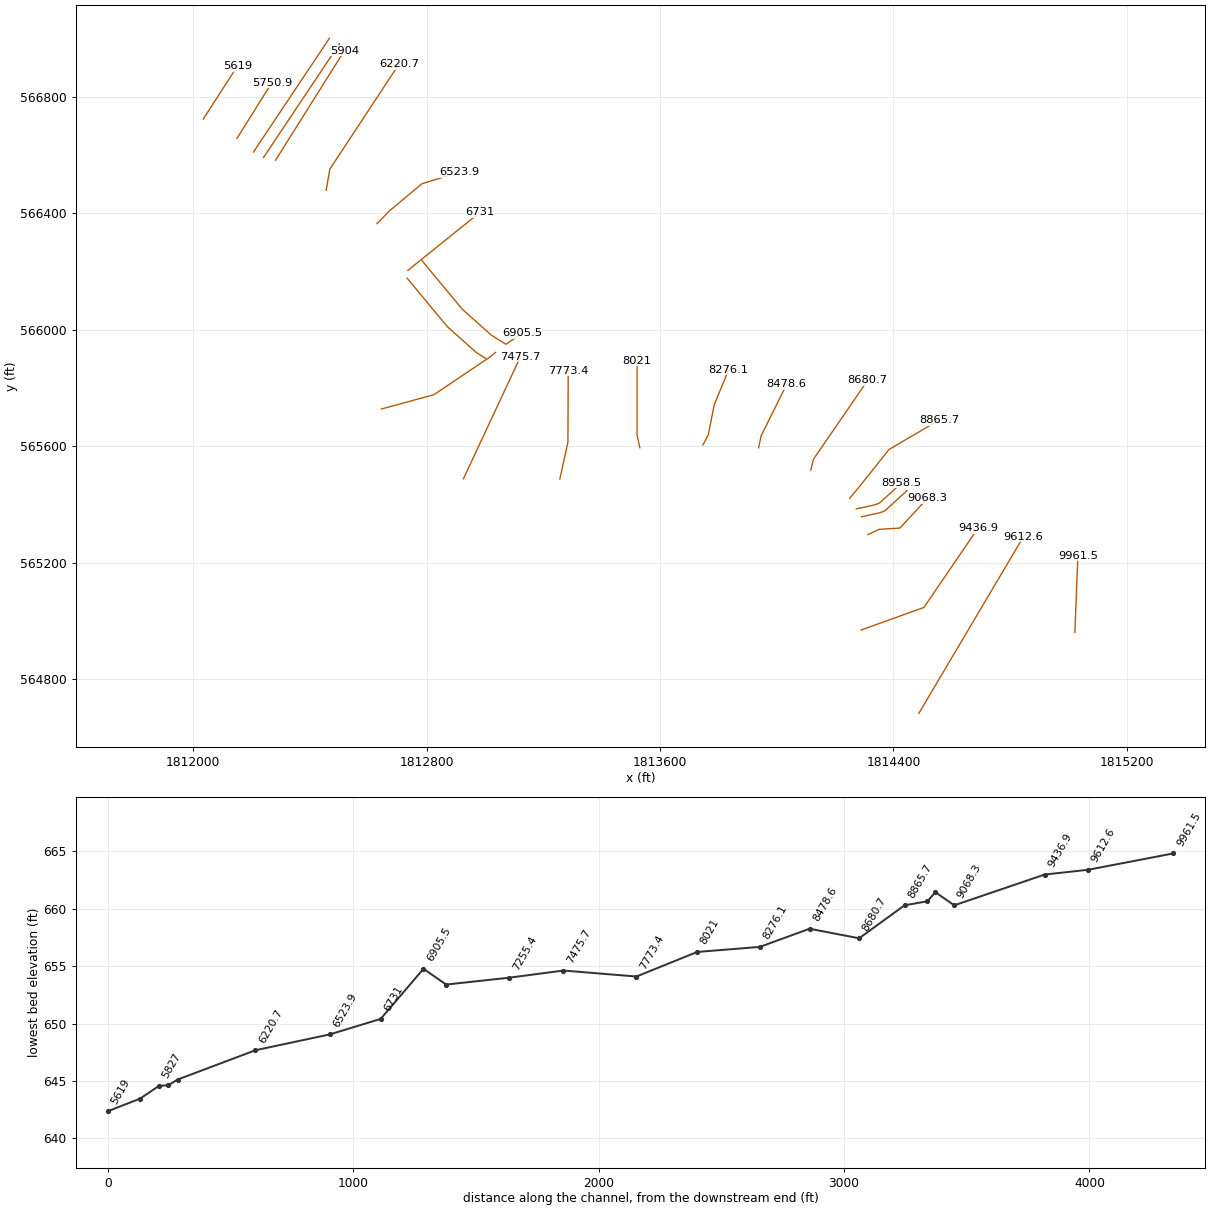
HEC-RAS study LTHRWDCK.prj: LTHRWDCK

--- LTHRWDCK.g01 (geometry) --- (continued)

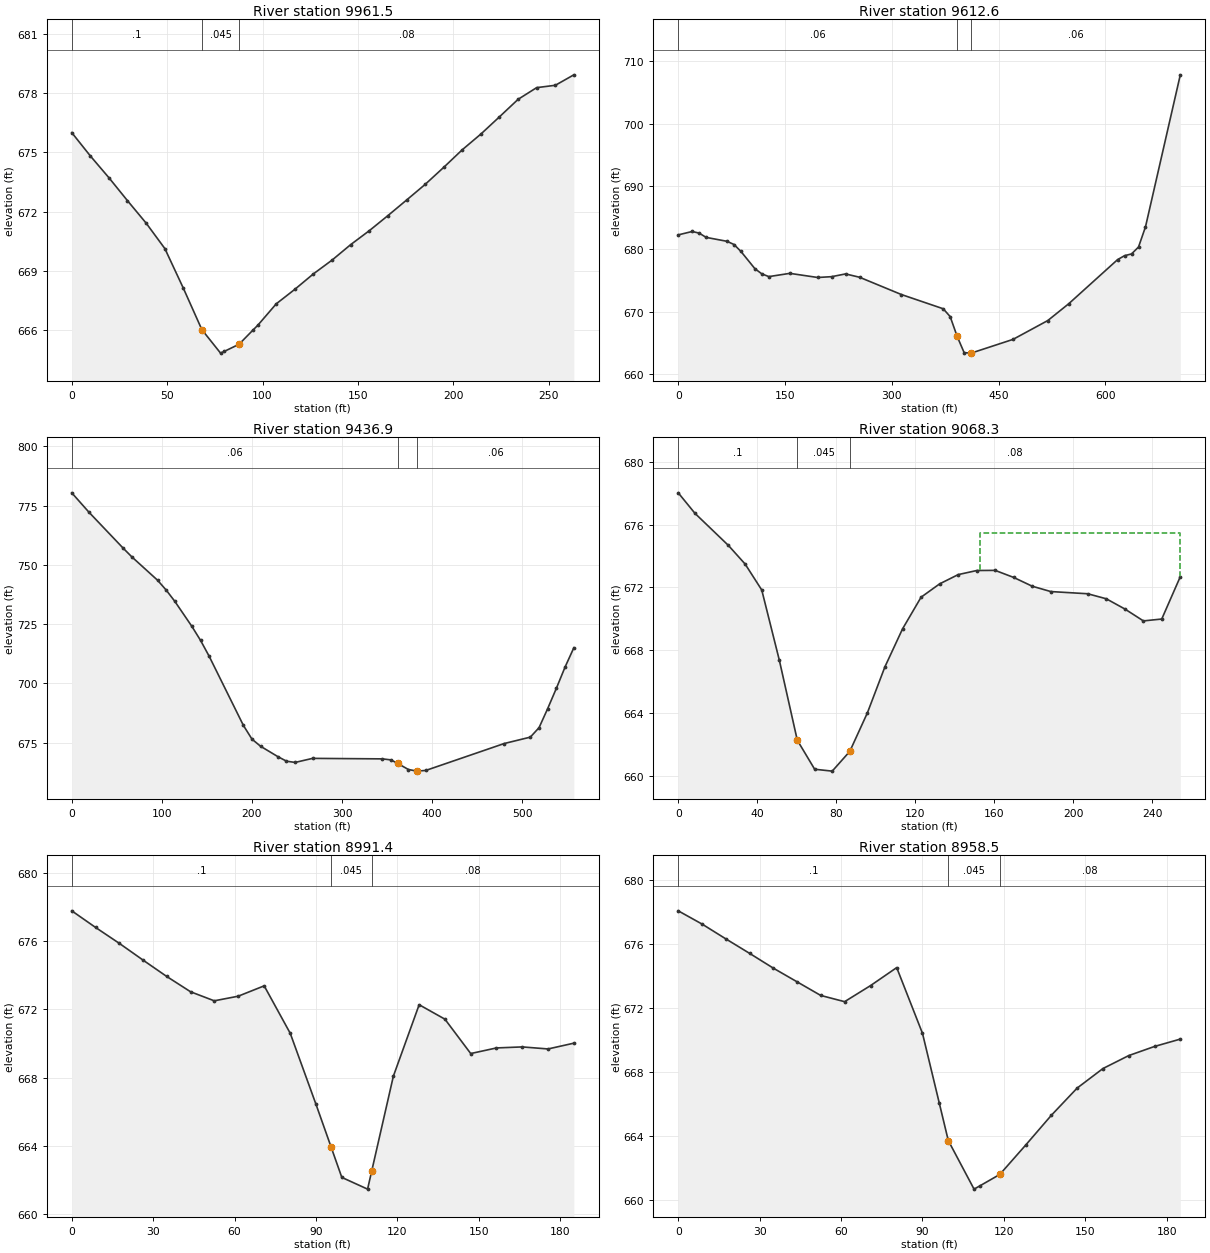
Type RM Length L Ch R = 1 ,9961.5  ,359.7,348.9,337.6
XS GIS Cut Line= 2
      1815022.05       564960.51     1815032.466      565223.531
#Sta/Elev= 30
       0     676     9.8  674.81    19.5  673.71    29.2  672.55      39  671.41
    48.8  670.12    58.5  668.11    68.2  666.01      78  664.82      80  664.91
    87.7  665.27      95  665.99    97.5  666.23   107.2  667.32     117  668.06
   126.7  668.84   136.5  669.54   146.2  670.32     156  671.03   165.7  671.79
   175.5  672.58   185.2  673.37     195  674.24   204.7  675.13   214.5  675.93
   224.2   676.8     234  677.69   243.7  678.28   253.5   678.4   263.2  678.93
#Mann= 3 , 0 , 0
       0      .1       0    68.2    .045       0    87.7     .08       0
Bank Sta=68.2,87.7
XS Rating Curve= 0 ,0
Exp/Cntr=0.3,0.1

Type RM Length L Ch R = 1 ,9612.6  ,176.7,175.6,174.2
XS GIS Cut Line= 2
     1814487.136      564682.446     1814845.834      565289.503
#Sta/Elev= 30
       0  682.26    19.6   682.8    29.4  682.54    39.2  681.86    68.6  681.23
    78.4  680.72    88.1  679.61   107.7  676.86   117.5  676.03   127.3   675.6
   156.7  676.12   195.9  675.46   215.4  675.59     235  676.03   254.6   675.5
   313.4  672.74   372.1  670.47   381.9  669.22   391.7  666.06   401.5  663.47
   411.3  663.39   470.1  665.58     519  668.59   548.4  671.27     617  678.31
   626.8  678.94   636.6  679.22   646.4  680.32   656.2  683.54   705.1   707.8
#Mann= 3 , 0 , 0
       0     .06       0   391.7    .045       0   411.3     .06       0
Bank Sta=391.7,411.3
XS Rating Curve= 0 ,0
Exp/Cntr=0.3,0.1

Type RM Length L Ch R = 1 ,9436.9  ,390.8,368.6,346.8
XS GIS Cut Line= 3
     1814289.654      564968.904     1814504.689      565046.447
     1814689.584      565318.149
#Sta/Elev= 30
       0  780.37      19  772.22    57.2  756.96    66.7  753.34    95.2  743.51
   104.8  739.34   114.3  734.63   133.3  724.03   142.9  718.14   152.4  711.49
   190.5  682.24     200  676.47   209.5  673.48   228.6  669.12   238.3  667.17
   247.9  666.65   267.2  668.36   344.6  668.15   354.2  667.72   361.8   666.2
   373.6  663.66   383.2  662.98   392.9  663.27   479.9  674.62   508.9  677.32
   518.6  681.32   528.2  689.38   537.9     698   547.6  707.01   557.2  715.02
#Mann= 3 , 0 , 0
       0     .06       0   361.8    .045       0   383.2     .06       0
Bank Sta=361.8,383.2
XS Rating Curve= 0 ,0
Exp/Cntr=0.3,0.1

Type RM Length L Ch R = 1 ,9068.3  ,60.1,76.9,92.5
XS GIS Cut Line= 4
     1814312.848      565296.447     1814351.043      565314.677
     1814422.223      565319.017     1814517.709      565422.315
#Sta/Elev= 27
       0  678.03     8.5  676.72    25.4  674.68    33.9  673.49    42.3  671.84
    51.2  667.37    60.3  662.27    69.1  660.42      78   660.3    86.9  661.56
    95.8  664.01   104.7  666.95   113.6  669.36     123  671.38   132.4  672.23
   141.8  672.82   151.2  673.08   160.5  673.09   169.9  672.64   179.3  672.08
   188.7  671.74   207.4   671.6   216.8  671.28   226.2  670.63   235.6  669.87
   244.9  669.99   254.3  672.69
#Mann= 3 , 0 , 0
       0      .1       0    60.3    .045       0    86.9     .08       0
#XS Ineff= 2 , 0
                          153.02          675.44
Permanent Ineff=
       F       F
Bank Sta=60.3,86.9
XS Rating Curve= 0 ,0
Exp/Cntr=0.3,0.1

Type RM Length L Ch R = 1 ,8991.4  ,33.4,32.9,32.6
XS GIS Cut Line= 4
     1814291.147      565358.079     1814351.043        565371.1
     1814369.272      565377.177     1814446.529      565447.489
#Sta/Elev= 23
       0   677.8     8.8  676.82    17.5  675.89    26.3   674.9      35  673.94
    43.8  673.04    52.5  672.51    61.3  672.78    70.9  673.39    80.5   670.6
      90  666.42    95.5  663.94    99.5  662.13     109  661.44   110.5  662.49
   118.5  668.08     128  672.28   137.5  671.43     147  669.41   156.5  669.74
     166   669.8   175.5  669.68     185  670.02
#Mann= 3 , 0 , 0
       0      .1       0    95.5    .045       0   110.5     .08       0
Bank Sta=95.5,110.5
XS Rating Curve= 0 ,0
Exp/Cntr=0.3,0.1

Type RM Length L Ch R = 1 ,8958.5  ,89.3,92.8,96.4
XS GIS Cut Line= 4
     1814272.918      565384.989     1814332.814       565398.01
     1814351.043      565404.086       1814428.3      565474.399
#Sta/Elev= 23
       0  678.05     8.8  677.22    17.5   676.3    26.3  675.39      35  674.47
    43.8  673.61    52.5  672.76    61.3  672.37    70.9  673.38    80.5   674.5
      90  670.39    96.2  666.02    99.5  663.69     109  660.65   111.2  660.86
   118.5  661.57     128   663.4   137.5  665.27     147  666.97   156.5  668.19
     166     669   175.5  669.57     185  670.03
#Mann= 3 , 0 , 0
       0      .1       0    99.5    .045       0   118.5     .08       0
Bank Sta=99.5,118.5
XS Rating Curve= 0 ,0
Exp/Cntr=0.3,0.1

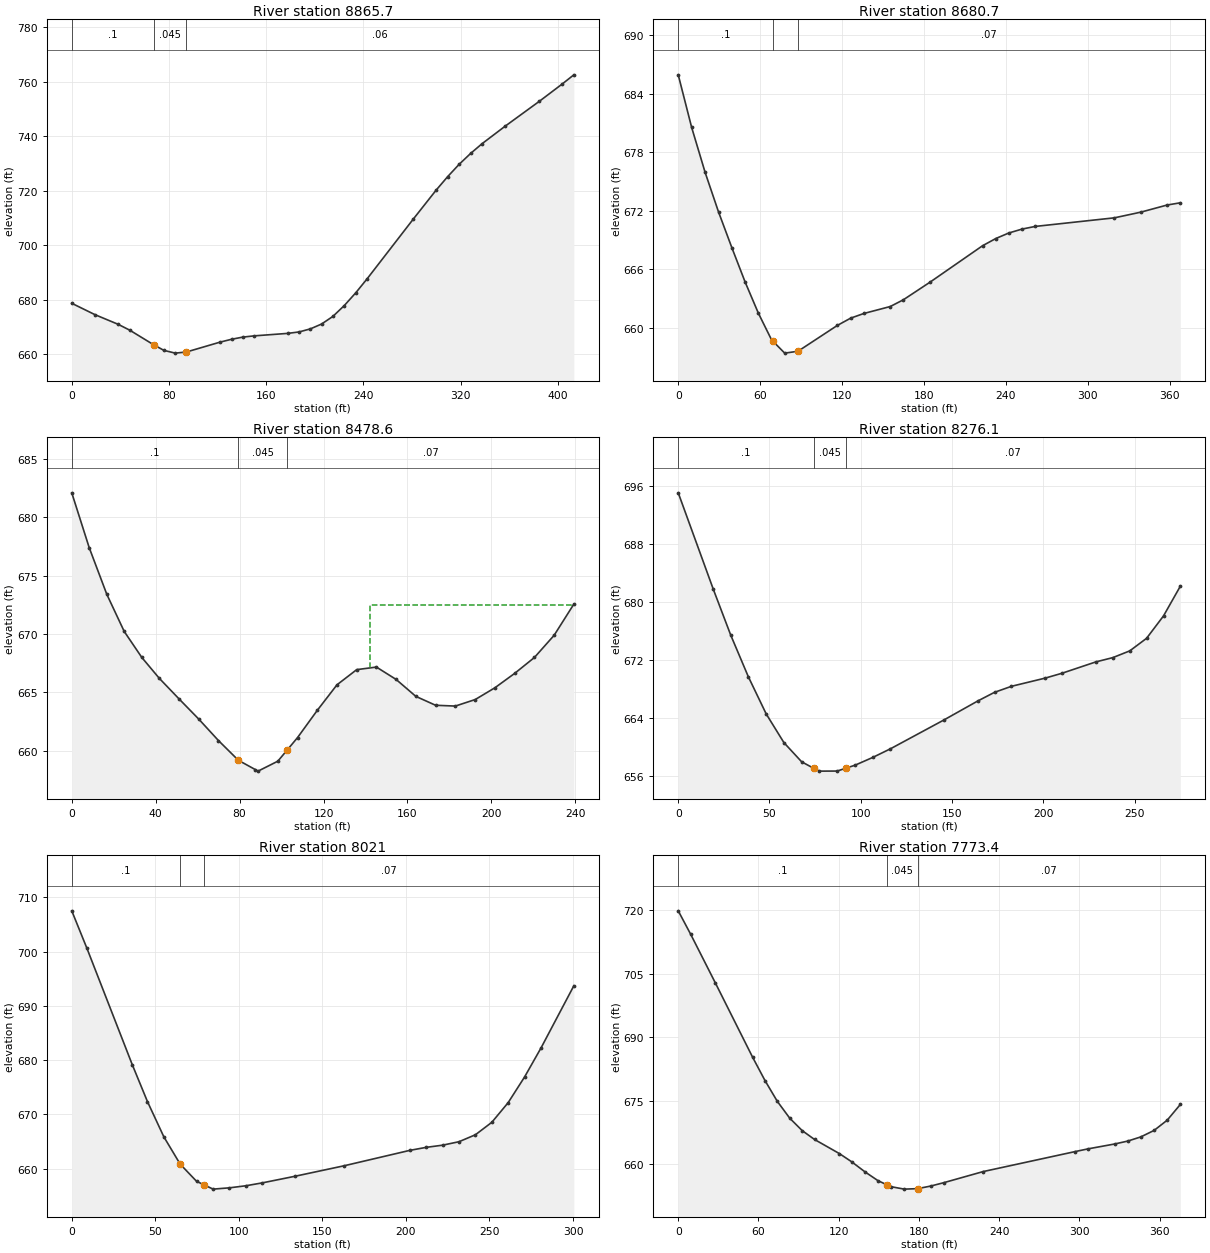
Type RM Length L Ch R = 1 ,8865.7  ,183.3,185,186.6
XS GIS Cut Line= 4
     1814250.348      565421.447     1814286.807      565465.718
     1814384.897      565588.982     1814555.904      565689.677
#Sta/Elev= 30
       0  678.62    19.1  674.44    38.2  670.89    47.8  668.72    67.3   663.4
    75.9   661.3    85.2   660.3    94.4  660.72   122.2  664.36   131.5  665.39
   140.8  666.19     150  666.64   177.8  667.56   187.1  668.09   196.4  669.21
   205.6  670.99   214.9  673.78   224.3  677.77   233.8  682.49   243.2  687.66
     281   709.5   299.9  720.19   309.4  725.16   318.8  729.67   328.3  733.69
   337.7  737.27   356.6  743.67     385   752.9   403.9  759.29   413.3   762.6
#Mann= 3 , 0 , 0
       0      .1       0    67.3    .045       0    94.4     .06       0
Bank Sta=67.3,94.4
XS Rating Curve= 0 ,0
Exp/Cntr=0.3,0.1

Type RM Length L Ch R = 1 ,8680.7  ,198.8,202,205.2
XS GIS Cut Line= 3
     1814116.668      565517.802     1814126.216      565555.996
      1814311.98      565826.829
#Sta/Elev= 26
       0  685.92     9.8  680.55    19.7  675.93    29.5  671.89    39.4  668.18
      49  664.71    58.7  661.52    68.4  658.78    69.5  658.63      78  657.43
    87.7  657.62   116.6  660.27   126.3  661.01     136  661.49   155.3   662.2
   164.9  662.89   184.3  664.68   222.9  668.42   232.6  669.16   242.2  669.73
   251.9  670.13   261.5   670.4   319.5  671.28   338.8  671.86   358.1  672.59
   367.8  672.82
#Mann= 3 , 0 , 0
       0      .1       0    69.5    .045       0    87.7     .07       0
Bank Sta=69.5,87.7
XS Rating Curve= 0 ,0
Exp/Cntr=0.3,0.1

Type RM Length L Ch R = 1 ,8478.6  ,197.2,202.5,207.9
XS GIS Cut Line= 3
     1813937.848      565595.058     1813946.529      565635.857
     1814034.202       565812.94
#Sta/Elev= 29
       0  682.09     8.3   677.4    16.7   673.4      25  670.22    33.4  667.99
    41.7  666.21    51.1  664.45    60.5  662.72    69.9  660.88    79.4  659.19
    87.5  658.39    88.8  658.26    98.2  659.11   102.5  660.03   107.6  661.13
     117  663.46   126.4  665.65   135.8  666.95   145.2  667.17   154.6  666.11
     164  664.66   173.4   663.9   182.8  663.83   192.3  664.39   201.7   665.4
   211.1  666.63   220.5  667.99   229.9  669.89   239.3  672.56
#Mann= 3 , 0 , 0
       0      .1       0    79.4    .045       0   102.5     .07       0
#XS Ineff= 2 , 0
                          141.94          672.45
Permanent Ineff=
       F       F
Bank Sta=79.4,102.5
XS Rating Curve= 0 ,0
Exp/Cntr=0.3,0.1

Type RM Length L Ch R = 1 ,8276.1  ,249.9,255.2,260.2
XS GIS Cut Line= 4
     1813746.876      565604.607     1813765.105      565638.461
     1813785.939      565743.496     1813835.418      565863.288
#Sta/Elev= 26
       0  695.03    19.2  681.75    28.8   675.4    38.4  669.69    48.2  664.56
    57.9  660.61    67.6  657.97   74.14  657.08    77.4  656.68    87.1  656.69
    91.7  657.07    96.9   657.5   106.6  658.57   116.3  659.76   145.5  663.72
     164  666.33   173.3  667.54   182.6  668.37   201.1   669.5   210.3  670.17
   228.8  671.73   238.1  672.32   247.4  673.25   256.6  674.98   265.9  678.07
   275.1  682.16
#Mann= 3 , 0 , 0
       0      .1       0   74.14    .045       0    91.7     .07       0
Bank Sta=74.14,91.7
XS Rating Curve= 0 ,0
Exp/Cntr=0.3,0.1

Type RM Length L Ch R = 1 ,8021    ,247.7,247.6,247.1
XS GIS Cut Line= 3
      1813530.73      565595.058     1813521.182      565639.329
     1813521.182      565894.538
#Sta/Elev= 24
       0  707.52     9.1  700.59    36.2  679.18    45.3  672.37    55.1  665.88
    64.9  660.84    74.7  657.68    79.3  657.01    84.6  656.24    94.4  656.48
   104.2  656.86     114  657.39   133.6  658.61   163.1  660.55   202.3  663.38
   212.2  663.94     222  664.34   231.8  664.98   241.6  666.26   251.4  668.55
   261.2  672.18     271   676.9   280.9  682.28   300.5  693.71
#Mann= 3 , 0 , 0
       0      .1       0    64.9    .045       0    79.3     .07       0
Bank Sta=64.9,79.3
XS Rating Curve= 0 ,0
Exp/Cntr=0.3,0.1

Type RM Length L Ch R = 1 ,7773.4  ,307.3,297.6,287.5
XS GIS Cut Line= 3
     1813256.425       565487.42     1813284.202      565614.156
      1813285.07      565859.815
#Sta/Elev= 28
       0  719.89     9.3  714.35    27.8  702.82    55.6  685.29    64.9  679.75
    74.1  674.84    83.4  670.86    92.7  667.93   101.9  665.84   120.5   662.5
   129.7  660.56   139.6  658.19   149.4  656.09     156  655.13   159.2  654.67
     169   654.1   178.9  654.21   188.7  654.82   198.5  655.62     228  658.25
   296.8  662.98   306.6  663.63   326.3  664.77   336.1  665.46   345.9  666.45
   355.8  667.98   365.6   670.4   375.4  674.11
#Mann= 3 , 0 , 0
       0      .1       0     156    .045       0   178.9     .07       0
Bank Sta=156,178.9
XS Rating Curve= 0 ,0
Exp/Cntr=0.3,0.1

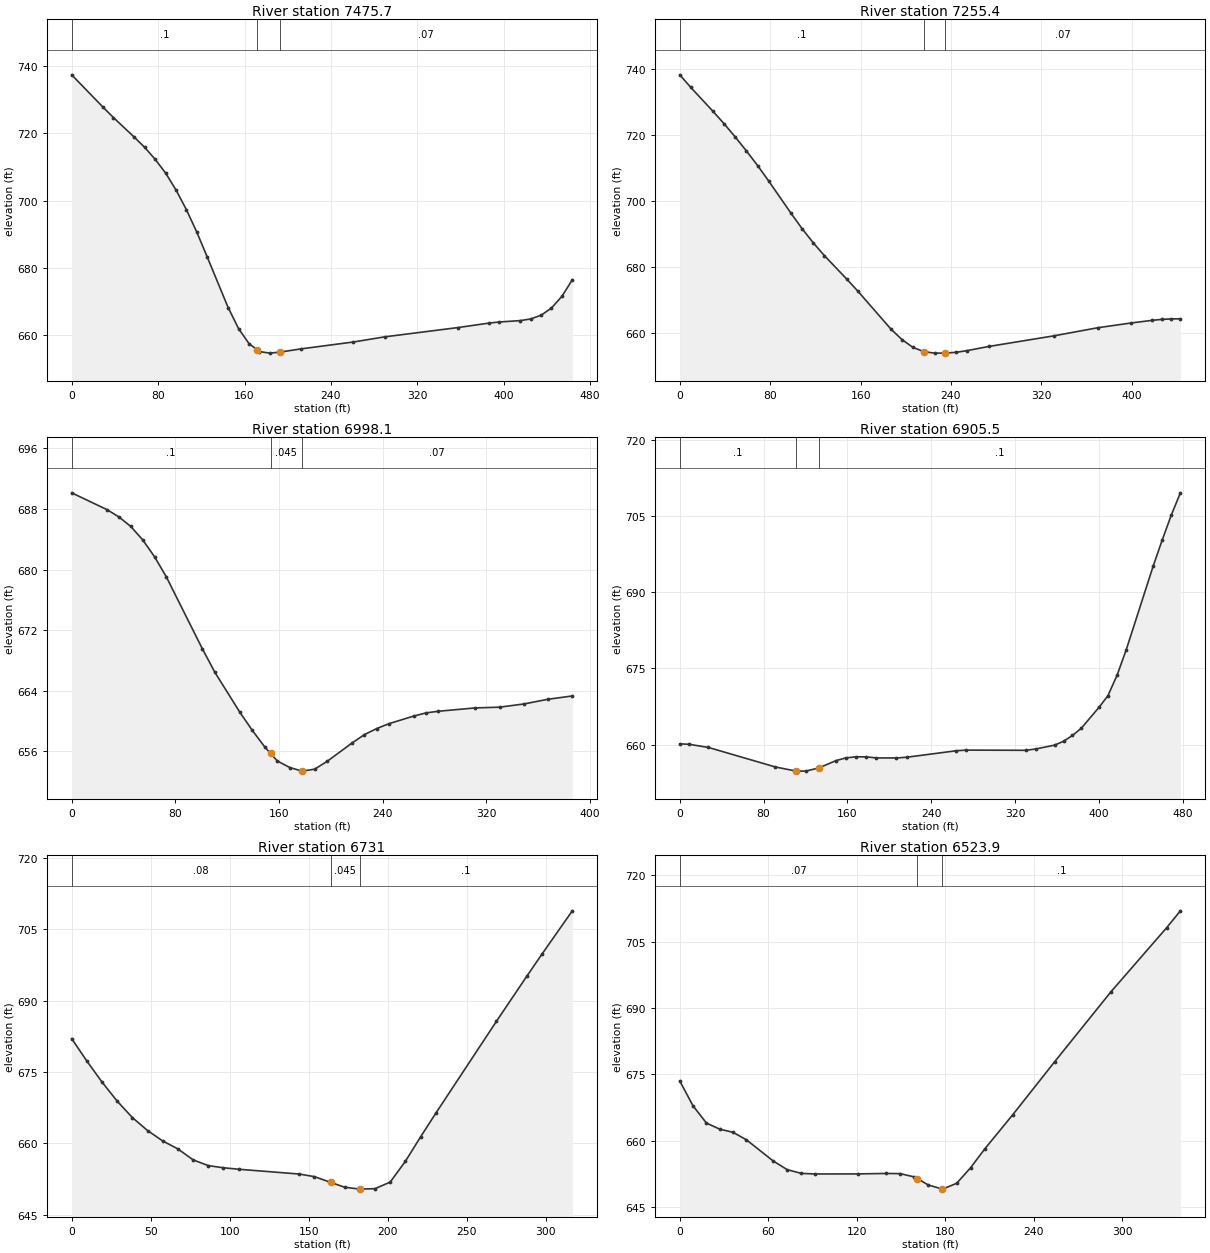
Type RM Length L Ch R = 1 ,7475.7  ,232.1,220.4,208
XS GIS Cut Line= 2
     1812925.939      565488.435     1813121.876      565908.427
#Sta/Elev= 30
       0  737.41      29  727.79    38.6  724.71    57.9  718.88    67.6  715.82
    77.2   712.3    86.9   708.2    96.6  703.13   106.2  697.29   115.9  690.55
   125.5   683.2   144.8  668.19   154.5  661.89   164.1  657.47   171.6  655.62
   173.8  655.08   183.4  654.62   193.1  654.94   212.4  655.89   260.7  657.93
   289.7  659.46   357.2  662.21   386.2  663.55   395.9  663.89   415.2  664.29
   424.8  664.79   434.5  665.89   444.1  668.04   453.8  671.52   463.4  676.44
#Mann= 3 , 0 , 0
       0      .1       0   171.6    .045       0   193.1     .07       0
Bank Sta=171.6,193.1
XS Rating Curve= 0 ,0
Exp/Cntr=0.3,0.1

Type RM Length L Ch R = 1 ,7255.4  ,293.5,257.3,220.3
XS GIS Cut Line= 4
     1812644.689      565728.019     1812825.001       565777.35
     1813016.841       565906.69     1813035.939      565922.315
#Sta/Elev= 30
       0  738.26     9.8  734.43    29.5  727.17    39.4  723.38    49.2  719.39
      59   715.2    68.9  710.78    78.7   706.1    98.4  696.37   108.2   691.7
   118.1  687.41   127.9  683.55   147.6  676.48   157.4  672.84   186.9  661.26
   196.6  658.12   206.2  655.77   215.9  654.46   225.5     654   235.1  654.02
   244.8  654.25   254.4  654.77   273.7  656.03   331.5  659.26   370.1   661.7
     399  663.11   418.3  663.94   426.5  664.21   434.8  664.36     443  664.39
#Mann= 3 , 0 , 0
       0      .1       0   215.9    .045       0   235.1     .07       0
Bank Sta=215.9,235.1
XS Rating Curve= 0 ,0
Exp/Cntr=0.3,0.1

Type RM Length L Ch R = 1 ,6998.1  ,92.2,92.6,94.1
XS GIS Cut Line= 5
     1812732.987      566177.524     1812791.147      566107.211
     1812871.008      566010.857     1812969.966      565922.315
     1813001.216       565902.35
#Sta/Elev= 30
       0  690.13    27.4   687.9    36.5  686.94    45.6  685.69    54.8  683.92
    63.9   681.7      73  679.05   100.9  669.52   110.5  666.44   129.8  661.16
   139.4  658.77     149  656.59   153.5  655.73   158.6  654.75   168.3  653.87
   177.9   653.4   187.5  653.66   197.1  654.69   216.4  657.12   225.9  658.22
   235.4  659.02   244.8  659.66   263.8  660.66   273.3  661.08   282.8   661.3
   311.2  661.74   330.2  661.84   349.2  662.27   367.7  662.89   386.3  663.32
#Mann= 3 , 0 , 0
       0      .1       0   153.5    .045       0   177.9     .07       0
Bank Sta=153.5,177.9
XS Rating Curve= 0 ,0
Exp/Cntr=0.3,0.1

Type RM Length L Ch R = 1 ,6905.5  ,135.1,174.5,212
XS GIS Cut Line= 6
     1812784.202       566237.42     1812842.362      566167.107
     1812922.223      566070.753     1813021.182      565982.211
       1813071.5      565950.559      1813128.82      565989.156
#Sta/Elev= 30
       0  660.14     9.1  660.05    27.4  659.43    91.2  655.59   110.5   654.8
   120.1  654.77   132.8   655.4     149  656.84   158.6  657.38   168.3  657.59
   177.9  657.58   187.5  657.37   206.8  657.36   216.4   657.5   263.8  658.78
   273.3  658.91   330.2  658.87   339.7  659.13   357.7  659.89   366.2  660.65
   374.7  661.79   383.2  663.23   400.1  667.34   408.6  669.64   417.3  673.66
   425.9  678.58   451.8  695.17   460.5  700.35   469.1  705.22   477.7  709.56
#Mann= 3 , 0 , 0
       0      .1       0   110.5    .045       0   132.8      .1       0
Bank Sta=110.5,132.8
XS Rating Curve= 0 ,0
Exp/Cntr=0.3,0.1

Type RM Length L Ch R = 1 ,6731    ,208.3,207.1,206.9
XS GIS Cut Line= 2
     1812735.591      566204.433     1812982.119      566403.218
#Sta/Elev= 26
       0  682.03     9.6  677.32    19.2   672.9    28.8  668.89    38.4  665.44
      48  662.72    57.6  660.53    67.2  658.86    76.8  656.56    86.4  655.35
      96   654.9   105.6  654.59     144  653.58   153.6  653.03   163.8  651.83
   172.7  650.81   182.3  650.41   191.9  650.51   201.5  651.89   211.1  656.26
   220.7  661.38   230.3  666.34   268.7  685.67   287.9  695.14   297.5  699.79
   316.7  708.89
#Mann= 3 , 0 , 0
       0     .08       0   163.8    .045       0   182.3      .1       0
Bank Sta=163.8,182.3
XS Rating Curve= 0 ,0
Exp/Cntr=0.3,0.1

Type RM Length L Ch R = 1 ,6523.9  ,295.8,303.2,310.4
XS GIS Cut Line= 4
     1812629.689      566365.024     1812673.959      566410.163
     1812784.202      566502.177     1812910.939      566541.239
#Sta/Elev= 25
       0   673.5       9  667.87    18.1  663.98    27.1  662.61    36.1   661.9
    45.2   660.2    63.2  655.46    72.8  653.46    82.4  652.62    91.9  652.48
   120.7   652.5   139.8   652.6   149.4  652.56     159  651.82   161.1  651.42
   168.5     650   178.1  649.06   187.7  650.37   197.2  653.91   206.8  658.16
   225.8  665.89   254.2  677.86   292.1  693.56     330  708.09   339.4  711.94
#Mann= 3 , 0 , 0
       0     .07       0   161.1    .045       0   178.1      .1       0
Bank Sta=161.1,178.1
XS Rating Curve= 0 ,0
Exp/Cntr=0.3,0.1

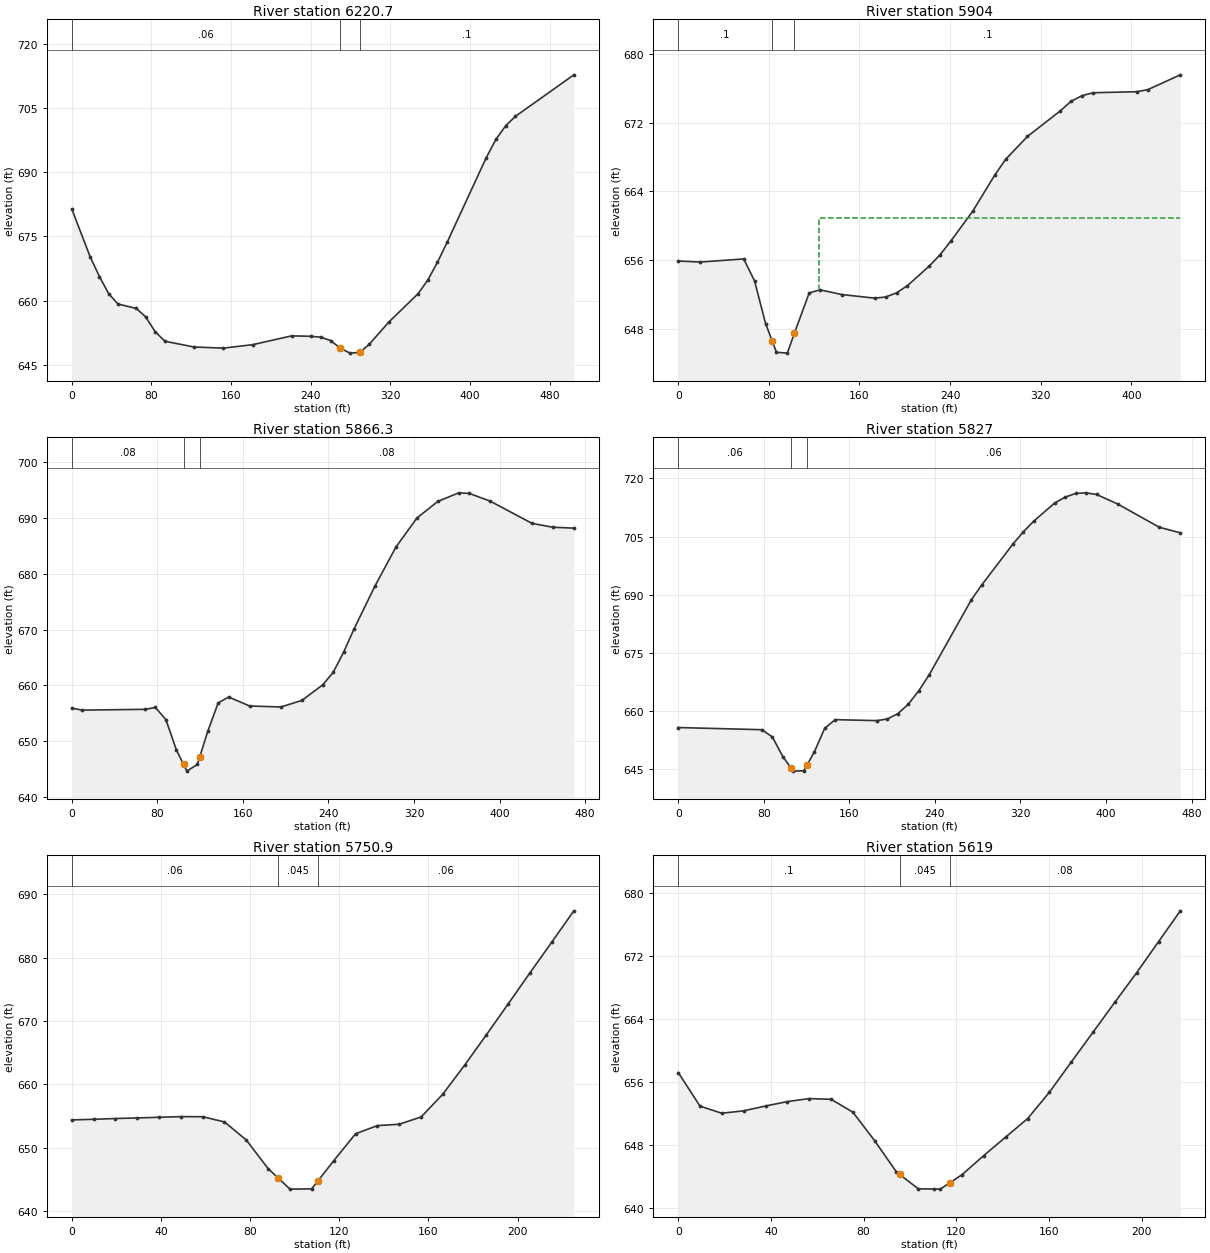
Type RM Length L Ch R = 1 ,6220.7  ,318,316.7,359.8
XS GIS Cut Line= 3
     1812455.209      566479.607      1812468.23      566552.524
     1812704.341      566911.899
#Sta/Elev= 30
       0  681.45    18.5  670.22    27.8  665.62      37  661.62    46.3   659.2
    64.8  658.14    74.1   656.2    83.8  652.68    93.6  650.46   122.9  649.11
   152.2  648.85   181.6  649.66   220.7  651.72   240.2  651.63     250  651.41
   259.8  650.63   269.5  648.87   279.3  647.68   289.1  647.85   298.8  649.78
   318.4  654.97   347.7   661.6   357.5  664.81   367.2  668.98     377   673.7
   416.1  693.44   425.9  697.76   435.7  700.95   445.4  703.14   504.1  712.87
#Mann= 3 , 0 , 0
       0     .06       0   269.5    .045       0   289.1      .1       0
Bank Sta=269.5,289.1
XS Rating Curve= 0 ,0
Exp/Cntr=0.3,0.1

Type RM Length L Ch R = 1 ,5904    ,38.3,37.7,37.3
XS GIS Cut Line= 2
     1812281.993      566582.966     1812517.453        566958.4
#Sta/Elev= 30
       0  655.87    19.3  655.75    57.8  656.11    67.4  653.54    77.1  648.58
   82.82646.5839    86.7  645.23    96.3  645.13   102.6  647.47   115.6  652.15
   125.2  652.51   144.5  651.96   173.4  651.54     183  651.67   192.7  652.16
   202.3     653   221.6  655.28   231.2  656.61   240.8  658.23   260.1  661.71
   279.4  665.89     289  667.72   308.3   670.4   337.2  673.37   346.8   674.5
   356.5  675.15   366.1  675.49   404.6  675.61   414.3  675.84   443.2  677.58
#Mann= 3 , 0 , 0
       0      .1       0   82.82    .045       0   102.6      .1       0
#XS Ineff= 2 , 0
                          124.45          660.85
Permanent Ineff=
       F       F
Bank Sta=82.82,102.6
XS Rating Curve= 0 ,0
Exp/Cntr=0.3,0.1

Type RM Length L Ch R = 1 ,5866.3  ,39.2,39.2,39.2
XS GIS Cut Line= 2
       1812240.8      566592.454     1812501.216      566983.079
#Sta/Elev= 30
       0  655.93     9.8  655.58    68.5  655.72    78.2  656.05      88  653.88
    97.8  648.46   104.5  645.85   107.6  644.64   117.4  645.83   119.5   647.1
   127.2  651.78   136.9  656.87   146.7  657.93   166.3  656.32   195.6  656.14
   215.2  657.32   234.7  660.11   244.5  662.37   254.3     666   264.1   670.2
   283.6  677.86   303.2  684.84   322.8  690.03   342.3     693   361.9  694.54
   371.7  694.43   391.2  693.06   430.4  689.06   449.9  688.37   469.5  688.21
#Mann= 3 , 0 , 0
       0     .08       0   104.5    .045       0   119.5     .08       0
Bank Sta=104.5,119.5
XS Rating Curve= 0 ,0
Exp/Cntr=0.3,0.1

Type RM Length L Ch R = 1 ,5827    ,75.5,76.1,76.8
XS GIS Cut Line= 2
     1812206.077        566610.9     1812466.494      567001.525
#Sta/Elev= 30
       0   655.8    78.2  655.24      88  653.38    97.8  648.32   105.6  645.34
   107.6  644.57   117.4  644.66   120.6  646.23   127.2  649.47   136.9  655.57
   146.7  657.83   185.8  657.58   195.6  658.01   205.4  659.37   215.2  661.83
     225  665.29   234.7  669.39   273.9  688.62   283.6  692.45     313  703.08
   322.8  706.23   332.5  708.98   352.1  713.65   361.9  715.16   371.7  716.11
   381.4  716.26   391.2  715.83   410.8   713.4   449.9  707.39   469.5  705.96
#Mann= 3 , 0 , 0
       0     .06       0   105.6    .045       0   120.6     .06       0
Bank Sta=105.6,120.6
XS Rating Curve= 0 ,0
Exp/Cntr=0.3,0.1

Type RM Length L Ch R = 1 ,5750.9  ,132.2,131.9,131.6
XS GIS Cut Line= 2
     1812149.615      566657.836     1812268.972      566848.808
#Sta/Elev= 26
       0  654.39     9.8  654.49    19.6  654.61    29.4   654.7    39.2  654.81
      49  654.91    58.8  654.89    68.5  654.07    78.3  651.21    88.1   646.7
    92.6  645.22    97.9  643.47   107.6  643.51   110.5644.8106   117.5  647.95
   127.3  652.21   137.1  653.49   146.9  653.71   156.7  654.86   166.4  658.44
   176.2  663.02     186  667.83   195.8  672.72   205.6  677.64   215.4  682.49
   225.2  687.38
#Mann= 3 , 0 , 0
       0     .06       0    92.6    .045       0   110.5     .06       0
Bank Sta=92.6,110.5
XS Rating Curve= 0 ,0
Exp/Cntr=0.3,0.1

Type RM Length L Ch R = 1 ,5619    ,259.2,261.9,262.9
XS GIS Cut Line= 2
     1812034.202      566724.399      1812151.39       566906.69
#Sta/Elev= 27
       0  657.18     9.4  652.91    18.8  652.01    28.3  652.32    37.7  652.93
    47.1  653.49    56.5  653.87      66  653.78    75.4  652.14    84.8  648.51
    94.2  644.54    95.5  644.25   103.6  642.41   110.5  642.38   113.1  642.37
  117.36643.2039   122.5  644.21   131.9  646.64   141.3  648.98   150.8  651.33
   160.2  654.68   169.6   658.5     179  662.29   188.4  666.09   197.9  669.88
   207.3   673.8   216.7  677.72
#Mann= 3 , 0 , 0
       0      .1       0    95.5    .045       0  117.36     .08       0
Bank Sta=95.5,117.36
XS Rating Curve= 0 ,0
Exp/Cntr=0.3,0.1