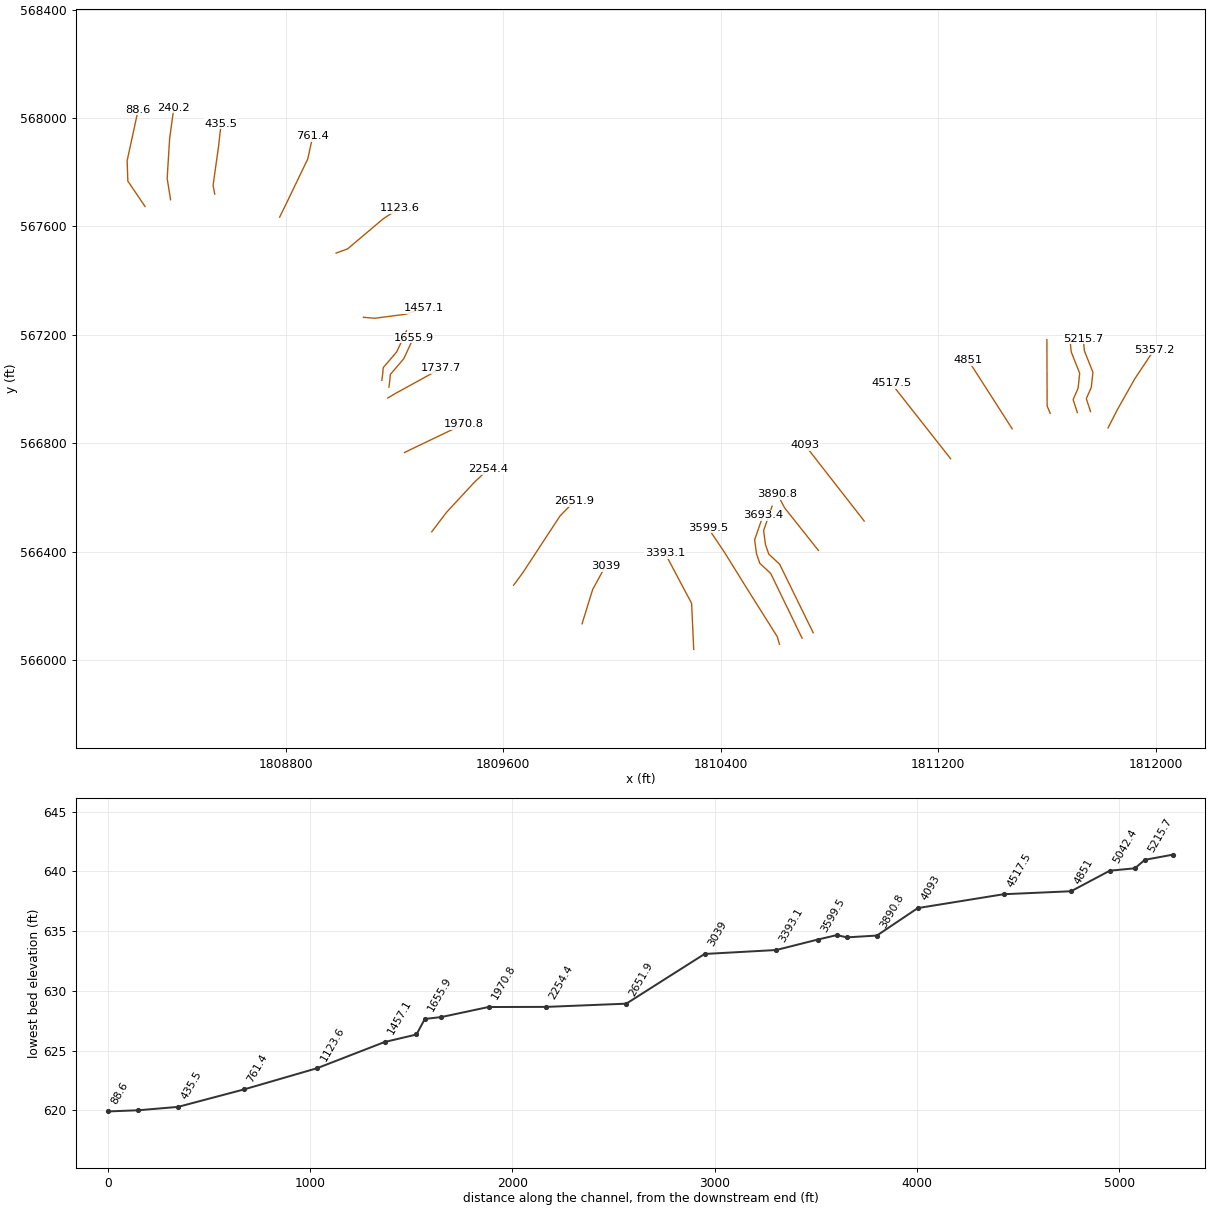
HEC-RAS study LTHRWDCK.prj: LTHRWDCK

--- LTHRWDCK.g01 (geometry) --- (continued)

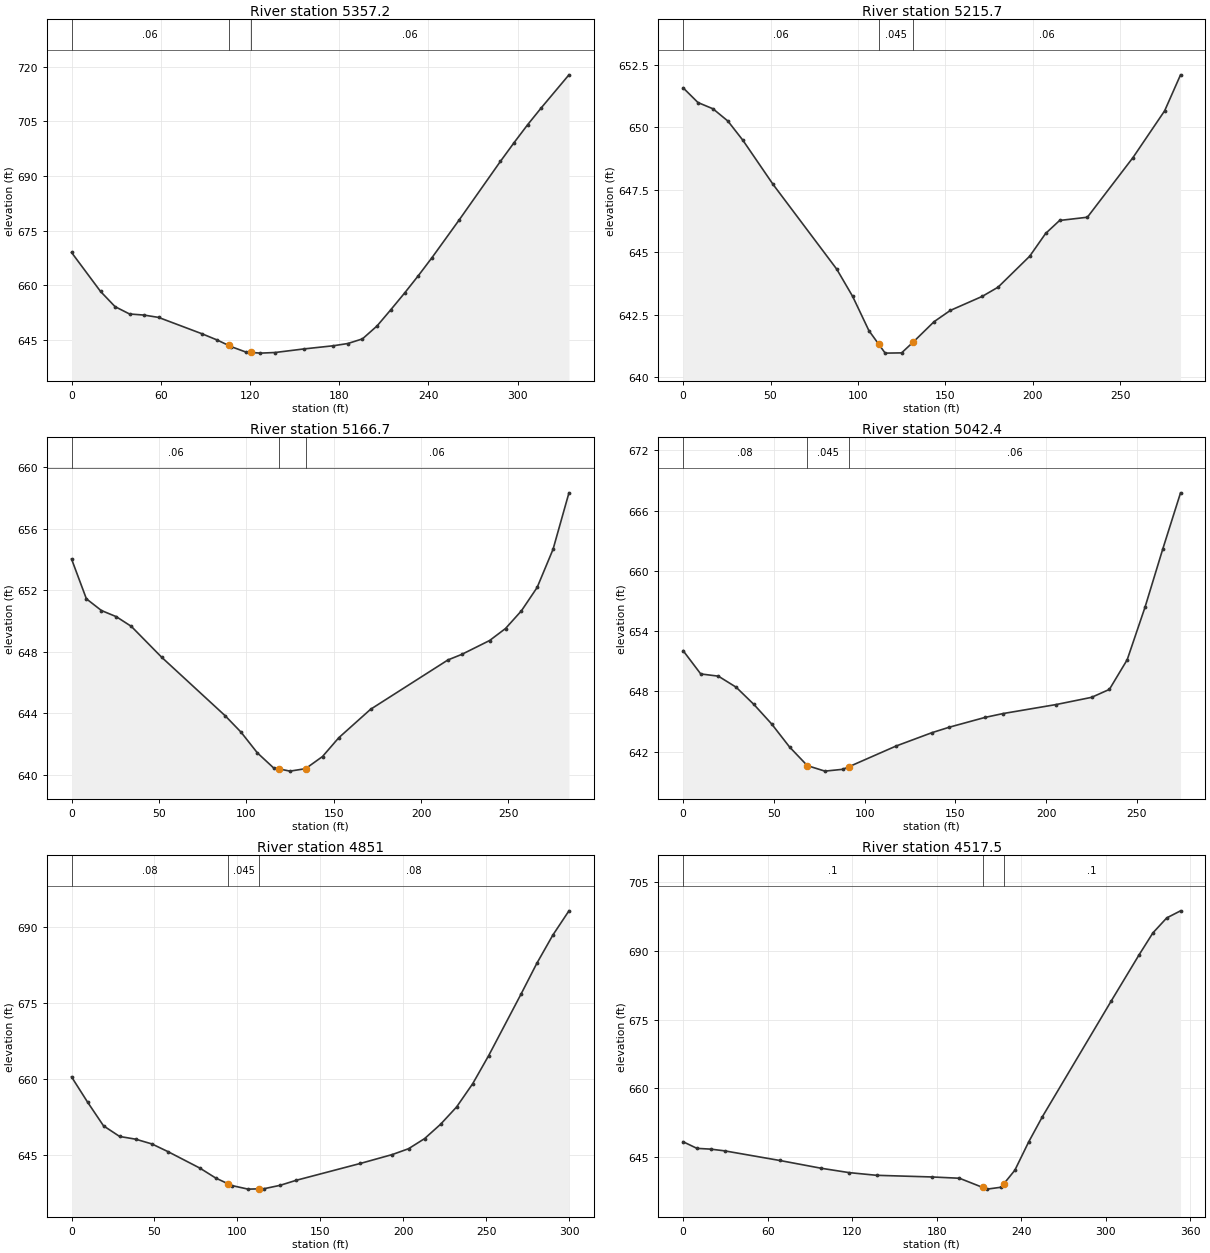
Type RM Length L Ch R = 1 ,5357.2  ,133,141.5,150.6
XS GIS Cut Line= 4
     1811824.133      566856.343     1811859.723      566925.788
     1811922.223      567036.899     1811993.404      567144.538
#Sta/Elev= 29
       0  669.01    19.5  658.32    29.3  654.14      39  652.14    48.8  651.83
    58.5   651.2    87.8   646.7    97.6  645.06   105.7  643.51   107.4  643.18
   117.3  641.69   120.7  641.59   127.1   641.4   136.9  641.57   156.5  642.56
   176.1  643.42   185.9  644.04   195.7  645.31   205.5  648.85   214.7  653.27
     224  657.86   233.2   662.6   242.4  667.55   260.8  677.95   288.5  693.99
   297.7  699.13   306.9  704.09   316.1  708.73   334.6  717.72
#Mann= 3 , 0 , 0
       0     .06       0   105.7    .045       0   120.7     .06       0
Bank Sta=105.7,120.7
XS Rating Curve= 0 ,0
Exp/Cntr=0.3,0.1

Type RM Length L Ch R = 1 ,5215.7  ,49.1,49,48.9
XS GIS Cut Line= 6
     1811759.897      566916.239     1811744.272      566963.982
     1811762.501      567005.649     1811768.577      567061.204
     1811737.327      567140.197     1811732.987      567185.336
#Sta/Elev= 24
       0  651.58     8.5  650.99    17.1  650.74    25.6  650.25    34.2  649.48
    51.5  647.71    87.9  644.32      97  643.23   106.3  641.86  111.87 641.321
   115.6  640.96     125  640.97   131.6   641.4   143.6  642.22   152.9  642.67
   171.1  643.23   180.2   643.6   198.3  644.84   207.4  645.75   215.4  646.27
   231.3   646.4   257.4  648.79   275.5  650.66   284.6   652.1
#Mann= 3 , 0 , 0
       0     .06       0  111.87    .045       0   131.6     .06       0
Bank Sta=111.87,131.6
XS Rating Curve= 0 ,0
Exp/Cntr=0.3,0.1

Type RM Length L Ch R = 1 ,5166.7  ,121.7,124.2,126.5
XS GIS Cut Line= 6
     1811711.286      566912.767     1811695.661       566960.51
      1811713.89      567002.177     1811719.966      567057.732
     1811688.716      567136.725     1811684.376      567181.864
#Sta/Elev= 24
       0  654.04     8.5  651.45    17.1  650.69    25.6  650.29    34.2  649.66
    51.5  647.66    87.9  643.85      97  642.78   106.3  641.44   115.6  640.46
   118.9  640.39     125  640.25   133.9  640.41   143.6   641.2   152.9  642.42
   171.1  644.27   215.4  647.48   223.3  647.84   239.2  648.74   248.3  649.52
   257.4  650.67   266.4  652.19   275.5  654.67   284.6  658.34
#Mann= 3 , 0 , 0
       0     .06       0   118.9    .045       0   133.9     .06       0
Bank Sta=118.9,133.9
XS Rating Curve= 0 ,0
Exp/Cntr=0.3,0.1

Type RM Length L Ch R = 1 ,5042.4  ,178.2,191.4,205.6
XS GIS Cut Line= 3
     1811611.459      566910.163     1811600.175      566937.072
     1811599.307      567181.864
#Sta/Elev= 23
       0  652.05     9.7  649.73    19.4  649.51    29.2  648.41      39  646.69
    48.8  644.74    58.6  642.46    68.4   640.6    78.1  640.05    87.9  640.23
    91.1  640.47   117.3  642.55   136.9  643.87   146.7  644.43   166.3   645.4
   176.1  645.78   205.4  646.68     225   647.4   234.8  648.19   244.6  651.14
   254.4  656.36   264.2  662.17     274  667.77
#Mann= 3 , 0 , 0
       0     .08       0    68.4    .045       0    91.1     .06       0
Bank Sta=68.4,91.1
XS Rating Curve= 0 ,0
Exp/Cntr=0.3,0.1

Type RM Length L Ch R = 1 ,4851    ,331.9,333.5,333.4
XS GIS Cut Line= 2
     1811471.702      566852.871     1811310.244      567105.475
#Sta/Elev= 28
       0  660.48     9.7  655.48    19.3  650.81      29  648.72    38.7  648.18
    48.4  647.25      58  645.75    77.4  642.47      87   640.5    94.3  639.39
    96.7  639.03   106.4  638.33   113.2638.3849     116  638.41   125.7  639.08
   135.4  640.07   174.1   643.4   193.4  645.16   203.1   646.3   212.8   648.3
   222.4  651.12   232.1  654.55   241.8  659.14   251.4  664.67   270.8  676.74
   280.4  682.86   290.1  688.46   299.8  693.24
#Mann= 3 , 0 , 0
       0     .08       0    94.3    .045       0   113.2     .08       0
Bank Sta=94.3,113.2
XS Rating Curve= 0 ,0
Exp/Cntr=0.3,0.1

Type RM Length L Ch R = 1 ,4517.5  ,424.4,424.5,424.2
XS GIS Cut Line= 2
      1811245.14      566742.628     1811027.258      567020.406
#Sta/Elev= 22
       0   648.4     9.8  646.96    19.6  646.79    29.4  646.42    68.6  644.32
    98.1  642.62   117.7  641.68   137.3  641.09   176.5  640.73   196.1  640.45
   212.6  638.45   215.7  638.08   225.6  638.49   227.6  639.25   235.4  642.19
   245.2  648.35     255  653.88     304  679.16   323.6  689.13   333.4   693.9
   343.2  697.16     353   698.7
#Mann= 3 , 0 , 0
       0      .1       0   212.6    .045       0   227.6      .1       0
Bank Sta=212.6,227.6
XS Rating Curve= 0 ,0
Exp/Cntr=0.3,0.1

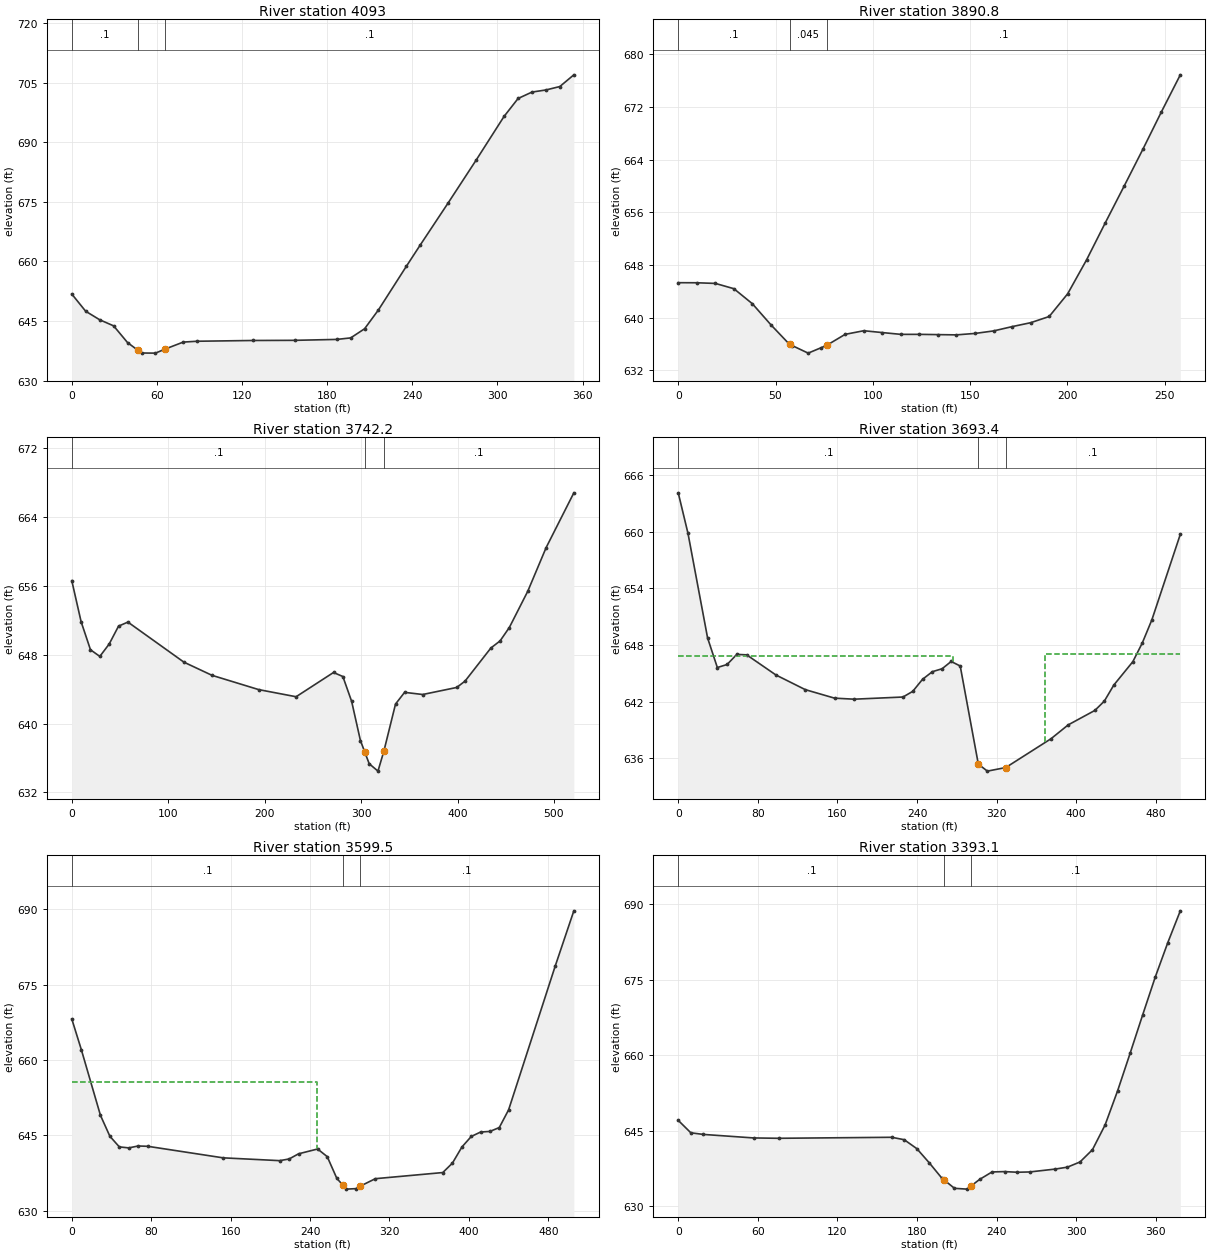
Type RM Length L Ch R = 1 ,4093    ,202,202.2,202.4
XS GIS Cut Line= 2
     1810927.432      566512.593     1810710.418      566792.107
#Sta/Elev= 27
       0  651.79     9.8  647.46    19.7  645.31    29.5  643.78    39.3  639.58
   46.77637.5956    49.2  636.95      59  636.92    65.8  637.94    78.6   639.7
    88.5  639.91   127.8   640.1   157.3  640.14   186.8  640.37   196.6  640.75
   206.4  643.05   216.2  647.81   235.9   658.8   245.7  664.16   265.4  674.76
   285.1  685.52   304.7  696.47   314.6  700.99   324.4   702.6   334.2  703.13
     344  703.99   353.9  706.94
#Mann= 3 , 0 , 0
       0      .1       0   46.77    .045       0    65.8      .1       0
Bank Sta=46.77,65.8
XS Rating Curve= 0 ,0
Exp/Cntr=0.3,0.1

Type RM Length L Ch R = 1 ,3890.8  ,145,148.6,152.2
XS GIS Cut Line= 3
     1810759.029      566404.086     1810634.897      566561.204
     1810607.987       566612.42
#Sta/Elev= 30
       0  645.31     9.5   645.3    19.1   645.2    28.6   644.4    38.1  642.12
    47.7   638.9    57.2  635.95    58.6  635.76    66.8  634.62    73.6  635.46
    76.3   635.8    85.8  637.47    95.4  638.02   104.9  637.74   114.4  637.47
     124  637.47   133.5  637.43     143  637.39   152.6  637.61   162.1  637.99
   171.6  638.64   181.2  639.24   190.7  640.18   200.2  643.63   209.9  648.77
   219.5  654.38   229.2  659.96   238.8  665.53   248.4  671.25   258.1  676.86
#Mann= 3 , 0 , 0
       0      .1       0    57.2    .045       0    76.3      .1       0
Bank Sta=57.2,76.3
XS Rating Curve= 0 ,0
Exp/Cntr=0.3,0.1

Type RM Length L Ch R = 1 ,3742.2  ,49,48.8,44
XS GIS Cut Line= 6
     1810739.932      566100.267     1810616.668      566352.871
     1810576.737      566390.197     1810564.584      566425.788
      1810557.64      566477.003      1810588.89      566567.281
#Sta/Elev= 30
       0  656.62     9.7  651.84    19.4  648.58    29.1  647.81    38.8  649.25
    48.5  651.33    58.2   651.8   116.3  647.14   145.4  645.61   193.8  643.95
   232.6  643.12   271.4  645.94   281.1  645.47   290.2  642.58   299.3  638.03
   303.8  636.69   308.4  635.33   317.5  634.47  323.65636.8068   335.7  642.27
   345.1  643.63   363.9  643.38   399.2   644.2   407.8  644.94   434.6  648.79
   444.1  649.61   453.7  651.17   472.8  655.38   491.9  660.47   520.6  666.83
#Mann= 3 , 0 , 0
       0      .1       0   303.8    .045       0  323.65      .1       0
Bank Sta=303.8,323.65
XS Rating Curve= 0 ,0
Exp/Cntr=0.3,0.1

Type RM Length L Ch R = 1 ,3693.4  ,100,93.9,92.7
XS GIS Cut Line= 6
     1810699.133      566080.302     1810583.682      566319.017
     1810543.751      566356.343     1810531.598      566391.933
     1810524.654      566443.149     1810555.904      566533.427
#Sta/Elev= 30
       0   664.1     9.8  659.81    29.5  648.75    39.3  645.62    49.1  645.94
    58.9  647.01    68.8  646.96    98.2  644.83   127.7  643.28   157.1  642.38
   176.8  642.27   225.9   642.5   235.7   643.1   245.5  644.37   255.4  645.18
   265.2  645.49   274.3  646.26   283.4  645.78   301.6   635.4   310.7  634.66
   329.2  635.04   374.7  638.09   391.9  639.55   418.7  641.08   428.2  642.06
   437.8  643.77   456.9  646.24   466.4  648.22     476  650.66   504.6  659.71
#Mann= 3 , 0 , 0
       0      .1       0   301.6    .045       0   329.2      .1       0
#XS Ineff= 2 , 0
          275.82  646.83  368.82          647.05
Permanent Ineff=
       F       F
Bank Sta=301.6,329.2
XS Rating Curve= 0 ,0
Exp/Cntr=0.3,0.1

Type RM Length L Ch R = 1 ,3599.5  ,207.7,206.4,204.6
XS GIS Cut Line= 5
       1810615.8      566057.732     1810607.987       566085.51
     1810496.876      566262.593     1810415.279      566394.538
     1810352.779      566488.288
#Sta/Elev= 30
       0  668.18     9.6  662.08    28.9  648.98    38.4  644.81    47.9   642.7
    57.4   642.5    66.9  642.88    76.4  642.82   152.4  640.52   209.4  639.96
   218.9  640.29   228.4  641.32   247.6  642.28   257.3  640.76     267  636.42
  273.16 635.069   276.7  634.29   286.4  634.39   290.8  634.91   305.8  636.37
   373.7  637.59   383.4  639.47     393  642.69   402.4  644.78   411.8  645.66
   421.2  645.78   430.6  646.55     440  650.08   486.9  678.68   505.7   689.7
#Mann= 3 , 0 , 0
       0      .1       0  273.16    .045       0   290.8      .1       0
#XS Ineff= 2 , 0
          246.59  655.56
Permanent Ineff=
       F       F
Bank Sta=273.16,290.8
XS Rating Curve= 0 ,0
Exp/Cntr=0.3,0.1

Type RM Length L Ch R = 1 ,3393.1  ,371.8,354.1,334.6
XS GIS Cut Line= 3
     1810300.695      566038.635     1810292.883      566208.774
     1810195.661      566392.802
#Sta/Elev= 30
       0  647.06     9.5  644.59    18.9  644.27    56.8  643.57    75.7   643.5
   160.9   643.7   170.3  643.22   179.8  641.45   189.2  638.63   198.7  635.58
   200.5   635.2   208.2  633.57   217.6  633.41  220.73634.0426   227.1  635.33
   236.5  636.82     246  636.89   255.5  636.76   264.9  636.82   283.8  637.38
   293.3  637.77   302.8   638.8   312.2  641.24   321.7  646.14   331.2  652.97
   340.6   660.4   350.1  668.05   359.5  675.49     369  682.36   378.4  688.65
#Mann= 3 , 0 , 0
       0      .1       0   200.5    .045       0  220.73      .1       0
Bank Sta=200.5,220.73
XS Rating Curve= 0 ,0
Exp/Cntr=0.3,0.1

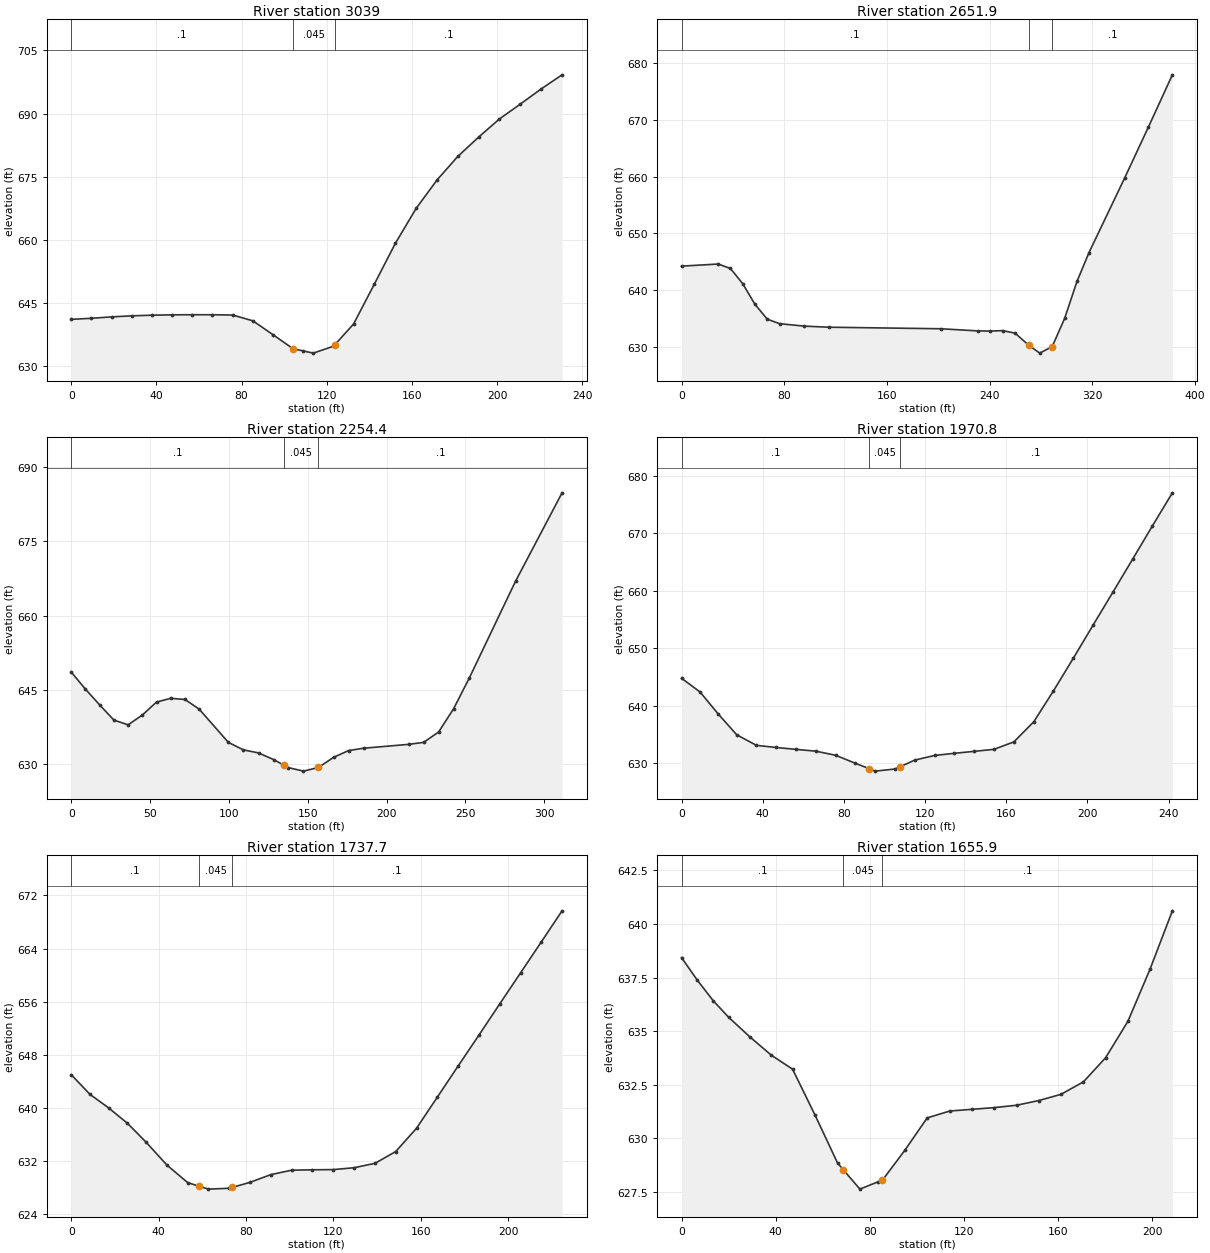
Type RM Length L Ch R = 1 ,3039    ,393.5,387.1,382
XS GIS Cut Line= 3
     1809890.105      566133.253     1809929.168      566259.989
     1809976.043      566345.927
#Sta/Elev= 27
       0   641.1     9.5  641.36      19  641.69    28.4  641.94    37.9  642.09
    47.4  642.18    56.8   642.2    66.3   642.2    75.8  642.13    85.3  640.76
    94.7  637.48   104.2  634.12   108.8  633.62   113.7  633.08   123.2  634.73
   123.8  635.07   132.6     640   142.4  649.52   152.2  659.15     162  667.48
   171.8  674.23   181.6  679.84   191.4  684.44   201.1  688.72   210.9  692.25
   220.7  695.85   230.5   699.2
#Mann= 3 , 0 , 0
       0      .1       0   104.2    .045       0   123.8      .1       0
Bank Sta=104.2,123.8
XS Rating Curve= 0 ,0
Exp/Cntr=0.3,0.1

Type RM Length L Ch R = 1 ,2651.9  ,401.9,397.5,393.3
XS GIS Cut Line= 4
     1809638.369      566275.614     1809672.223      566321.621
     1809809.376       566531.69     1809861.459      566584.642
#Sta/Elev= 23
       0  644.23    28.6   644.6    38.1  643.82    47.6  641.16    57.1  637.54
    66.8  634.89    76.4   634.1    95.7  633.67     115  633.48   201.9  633.21
   230.8  632.83   240.4   632.8   250.1  632.88   259.8  632.44   270.3  630.33
     279  628.92   288.7  630.07   298.4  635.03     308  641.54   317.3  646.58
   345.1  659.73   363.7  668.74   382.3   677.9
#Mann= 3 , 0 , 0
       0      .1       0   270.3    .045       0   288.7      .1       0
Bank Sta=270.3,288.7
XS Rating Curve= 0 ,0
Exp/Cntr=0.3,0.1

Type RM Length L Ch R = 1 ,2254.4  ,290.7,283.6,275.3
XS GIS Cut Line= 4
     1809337.397       566472.81     1809391.841      566544.711
      1809495.14       566656.69     1809545.487      566703.565
#Sta/Elev= 28
       0  648.64       9   645.2      18  642.02    27.1  638.94    36.1  637.99
    45.1  639.97    54.1  642.58    63.1  643.34    72.2   643.1    81.2  641.14
    99.7  634.44   109.2  632.94   118.8  632.32   128.3  630.99   134.9  629.85
   137.8  629.35   147.3  628.65   156.8  629.39   166.4  631.43   175.9   632.8
   185.4  633.27     214  634.05   223.5  634.45     233  636.54   242.5  641.23
   252.4  647.39   281.8  666.96   311.3  684.79
#Mann= 3 , 0 , 0
       0      .1       0   134.9    .045       0   156.8      .1       0
Bank Sta=134.9,156.8
XS Rating Curve= 0 ,0
Exp/Cntr=0.3,0.1

Type RM Length L Ch R = 1 ,1970.8  ,232.9,233.1,231.7
XS GIS Cut Line= 3
     1809237.327      566765.197     1809261.633       566777.35
     1809455.209      566870.232
#Sta/Elev= 28
       0  644.79     9.1  642.41    18.1  638.57    27.2  634.96    36.9  633.12
    46.7  632.75    56.4  632.42    66.2  632.11      76  631.39    85.7     630
    92.5  629.06    95.5  628.64   105.2  629.01   107.5  629.37     115  630.56
   124.8  631.37   134.5  631.74   144.3  632.08     154  632.43   163.8  633.73
   173.6  637.22   183.3  642.59   193.1  648.28   202.8  654.01   212.6  659.76
   222.4  665.54   232.1  671.29   241.9  677.02
#Mann= 3 , 0 , 0
       0      .1       0    92.5    .045       0   107.5      .1       0
Bank Sta=92.5,107.5
XS Rating Curve= 0 ,0
Exp/Cntr=0.3,0.1

Type RM Length L Ch R = 1 ,1737.7  ,72.3,81.9,93.3
XS GIS Cut Line= 3
     1809175.695      566966.586     1809205.209      566983.947
     1809371.876      567075.961
#Sta/Elev= 27
       0  645.03     8.6  642.06    17.1  640.03    25.7  637.72    34.2  634.89
    43.8  631.42    53.3  628.78    58.6  628.23    62.8   627.8    72.3  627.93
    73.6  628.05    81.8  628.82    91.4  629.99   100.9  630.65   110.4  630.71
   119.9  630.74   129.4  631.02     139  631.68   148.5  633.46     158  636.96
   167.5  641.63     177  646.31   186.6     651   196.1  655.69   205.6  660.35
   215.1  665.01   224.6  669.69
#Mann= 3 , 0 , 0
       0      .1       0    58.6    .045       0    73.6      .1       0
Bank Sta=58.6,73.6
XS Rating Curve= 0 ,0
Exp/Cntr=0.3,0.1

Type RM Length L Ch R = 1 ,1655.9  ,42.3,41.1,39.6
XS GIS Cut Line= 5
     1809180.026      567006.701      1809182.63      567026.666
     1809185.234      567053.576     1809234.713      567111.735
     1809270.303      567188.992
#Sta/Elev= 26
       0  638.43     6.7  637.38    13.4  636.43    20.1  635.64    29.2  634.72
    38.2  633.88    47.2  633.23    56.7   631.1    66.3  628.86    68.7  628.55
    75.8  627.64    83.7  627.99    85.4  628.06    94.9  629.45   104.4  630.96
     114  631.28   123.5  631.36     133  631.44   142.4  631.55   151.9  631.77
   161.3  632.06   170.8  632.64   180.2  633.76   189.7  635.46   199.1  637.89
   208.6  640.61
#Mann= 3 , 0 , 0
       0      .1       0    68.7    .045       0    85.4      .1       0
Bank Sta=68.7,85.4
XS Rating Curve= 0 ,0
Exp/Cntr=0.3,0.1

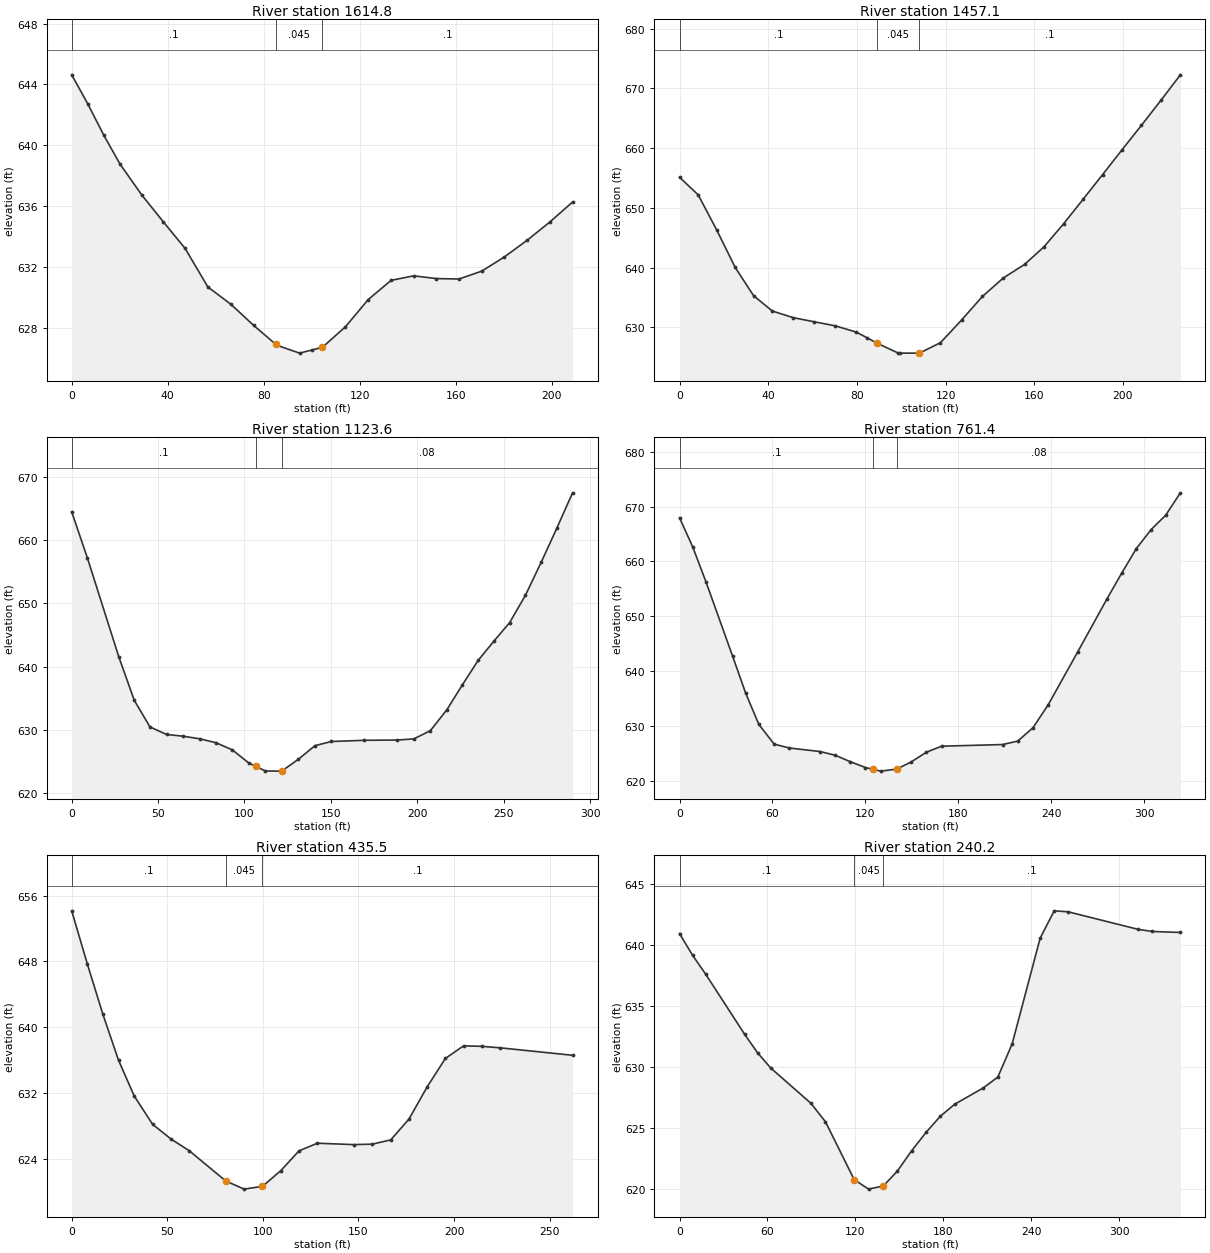
Type RM Length L Ch R = 1 ,1614.8  ,174.4,157.7,140.1
XS GIS Cut Line= 5
     1809153.984      567031.874     1809156.588      567051.839
     1809159.192      567078.749     1809208.671      567136.909
     1809244.262      567214.166
#Sta/Elev= 26
       0  644.63     6.7  642.72    13.4  640.65    20.1  638.77    29.2  636.73
    38.2  634.96    47.2  633.23    56.7  630.69    66.3  629.55    75.8  628.16
    84.9  626.93    85.4  626.86    94.9  626.34    99.9  626.54   104.4  626.72
     114  628.07   123.5  629.86     133  631.12   142.4  631.42   151.9  631.24
   161.3  631.21   170.8  631.73   180.2  632.66   189.7  633.76   199.1  634.95
   208.6  636.27
#Mann= 3 , 0 , 0
       0      .1       0    84.9    .045       0   104.4      .1       0
Bank Sta=84.9,104.4
XS Rating Curve= 0 ,0
Exp/Cntr=0.3,0.1

Type RM Length L Ch R = 1 ,1457.1  ,317.8,333.5,347.4
XS GIS Cut Line= 4
     1809086.286      567264.329     1809127.952      567260.857
       1809240.8      567275.614      1809307.64      567297.315
#Sta/Elev= 28
       0  655.12     8.4  652.19    16.7  646.36    25.1  640.05    33.4  635.32
    41.8  632.76    51.3  631.64    60.8  630.95    70.3  630.27    79.8  629.22
    84.6  628.27    89.2  627.35    98.7  625.71    99.6  625.71   108.2  625.71
   117.7  627.46   127.2  631.24   136.6  635.19   146.1   638.3   155.6  640.54
   164.4   643.5   173.2  647.33     182  651.43   190.8  655.56   199.5  659.68
   208.3   663.8   217.1  667.98   225.9  672.26
#Mann= 3 , 0 , 0
       0      .1       0    89.2    .045       0   108.2      .1       0
Bank Sta=89.2,108.2
XS Rating Curve= 0 ,0
Exp/Cntr=0.3,0.1

Type RM Length L Ch R = 1 ,1123.6  ,353.7,362.2,372.4
XS GIS Cut Line= 4
     1808985.591      567501.308     1809028.126      567516.933
     1809159.202      567628.045     1809219.966      567667.975
#Sta/Elev= 30
       0  664.47     9.1  657.18    27.2  641.62    36.2  634.71    45.3   630.5
    54.9  629.31    64.4  629.04      74  628.63    83.5  628.01      93  626.87
   102.6  624.78   106.5  624.28   112.1  623.55   121.5  623.52   131.2  625.39
   140.8  627.54   150.3   628.2   169.4  628.39   188.5  628.43     198  628.61
   207.6  629.91   217.2  633.23   226.2  637.18   235.3  641.02   244.4  644.06
   253.5  646.98   262.6  651.28   271.7  656.48   280.8  661.89   289.9  667.48
#Mann= 3 , 0 , 0
       0      .1       0   106.5    .045       0   121.5     .08       0
Bank Sta=106.5,121.5
XS Rating Curve= 0 ,0
Exp/Cntr=0.3,0.1

Type RM Length L Ch R = 1 ,761.4   ,317.3,326,332.7
XS GIS Cut Line= 4
     1808778.126      567634.121     1808800.695      567680.128
     1808881.425      567848.531     1808899.654      567931.864
#Sta/Elev= 29
       0  667.96     8.5  662.66    17.1  656.25    34.2  642.76    42.7  635.96
    51.2  630.26    61.1  626.66    70.9  625.96    90.6  625.32   100.4  624.65
   110.2  623.46     120   622.4   125.1  622.06   129.9  621.74   140.1   622.1
   149.5  623.41   159.4   625.2   169.2  626.29   208.5  626.59   218.3  627.22
   228.2  629.67     238  633.86     257  643.48   275.9  653.16   285.4  657.85
   294.9  662.36   304.4  665.81   313.8  668.43   323.3  672.52
#Mann= 3 , 0 , 0
       0      .1       0   125.1    .045       0   140.1     .08       0
Bank Sta=125.1,140.1
XS Rating Curve= 0 ,0
Exp/Cntr=0.3,0.1

Type RM Length L Ch R = 1 ,435.5   ,192.9,195.3,197
XS GIS Cut Line= 4
     1808539.411       567719.19     1808533.334      567751.308
       1808553.3       567893.67     1808562.848      567978.739
#Sta/Elev= 24
       0  654.17     8.2  647.68    16.3  641.58    24.5  635.97    32.7  631.62
    42.3  628.18    51.9  626.39    61.4  624.97    80.6  621.27    90.2  620.28
    99.8  620.62   109.4  622.53   118.9  624.94   128.5  625.87   147.7   625.7
   157.3  625.76   166.9  626.28   176.4   628.8     186  632.75   195.5   636.2
     205  637.73   214.5  637.67     224  637.49     262  636.58
#Mann= 3 , 0 , 0
       0      .1       0    80.6    .045       0    99.8      .1       0
Bank Sta=80.6,99.8
XS Rating Curve= 0 ,0
Exp/Cntr=0.3,0.1

Type RM Length L Ch R = 1 ,240.2   ,149.4,151.6,153.8
XS GIS Cut Line= 4
     1808377.084      567698.357     1808364.513      567777.322
     1808373.612      567924.052     1808389.237      568037.767
#Sta/Elev= 25
       0  640.92     8.9  639.14    17.8   637.6    44.4  632.68    53.3  631.15
    62.2  629.92    89.8  627.01    99.6  625.51   119.2  620.78     129     620
   139.1  620.26   148.6  621.47   158.4  623.14   168.2  624.64     178  625.97
   187.8  626.95   207.4  628.29   217.2  629.17     227  631.89   246.1  640.54
   255.7  642.78   265.2   642.7   313.1  641.26   322.6  641.09   341.8  641.01
#Mann= 3 , 0 , 0
       0      .1       0   119.2    .045       0   139.1      .1       0
Bank Sta=119.2,139.1
XS Rating Curve= 0 ,0
Exp/Cntr=0.3,0.1

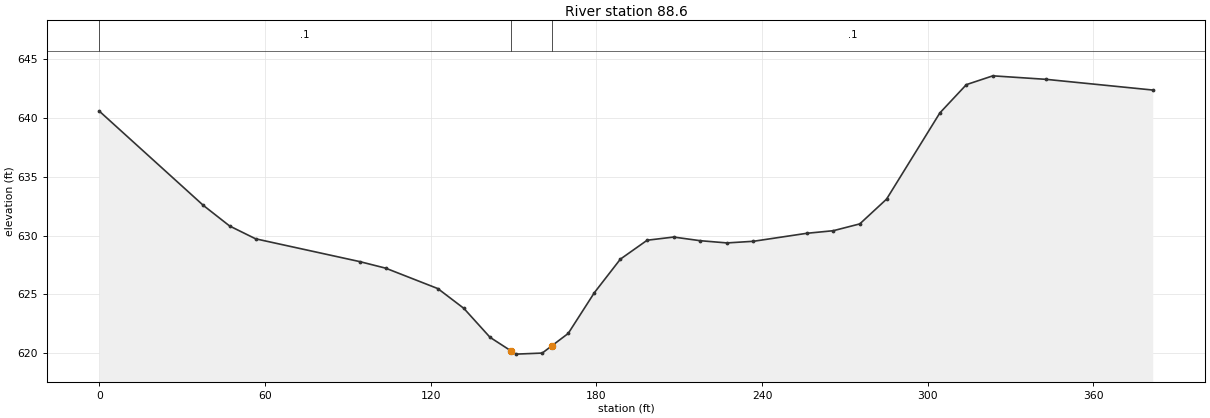
Type RM Length L Ch R = 1 ,88.6    ,91.3,88.6,85.9
XS GIS Cut Line= 4
     1808283.334      567673.183     1808219.966      567766.933
     1808217.362      567842.454     1808258.161      568030.822
#Sta/Elev= 30
       0  640.59    37.7  632.56    47.2  630.81    56.6  629.72    94.3  627.78
   103.7  627.22   122.6  625.48     132   623.8   141.5  621.33     149  620.19
   150.9   619.9   160.4  619.99     164  620.63   169.8  621.66   179.3  625.14
   188.7  627.99   198.4   629.6     208  629.87   217.6  629.56   227.3  629.37
   236.9  629.51   256.2  630.19   265.8  630.41   275.4  630.99   285.1   633.1
   304.4  640.44     314  642.85   323.6   643.6   342.9   643.3   381.5  642.39
#Mann= 3 , 0 , 0
       0      .1       0     149    .045       0     164      .1       0
Bank Sta=149,164
XS Rating Curve= 0 ,0
Exp/Cntr=0.3,0.1

Chan Stop Cuts=-1
Use User Specified Reach Order=0
Composite Channel Slope=5